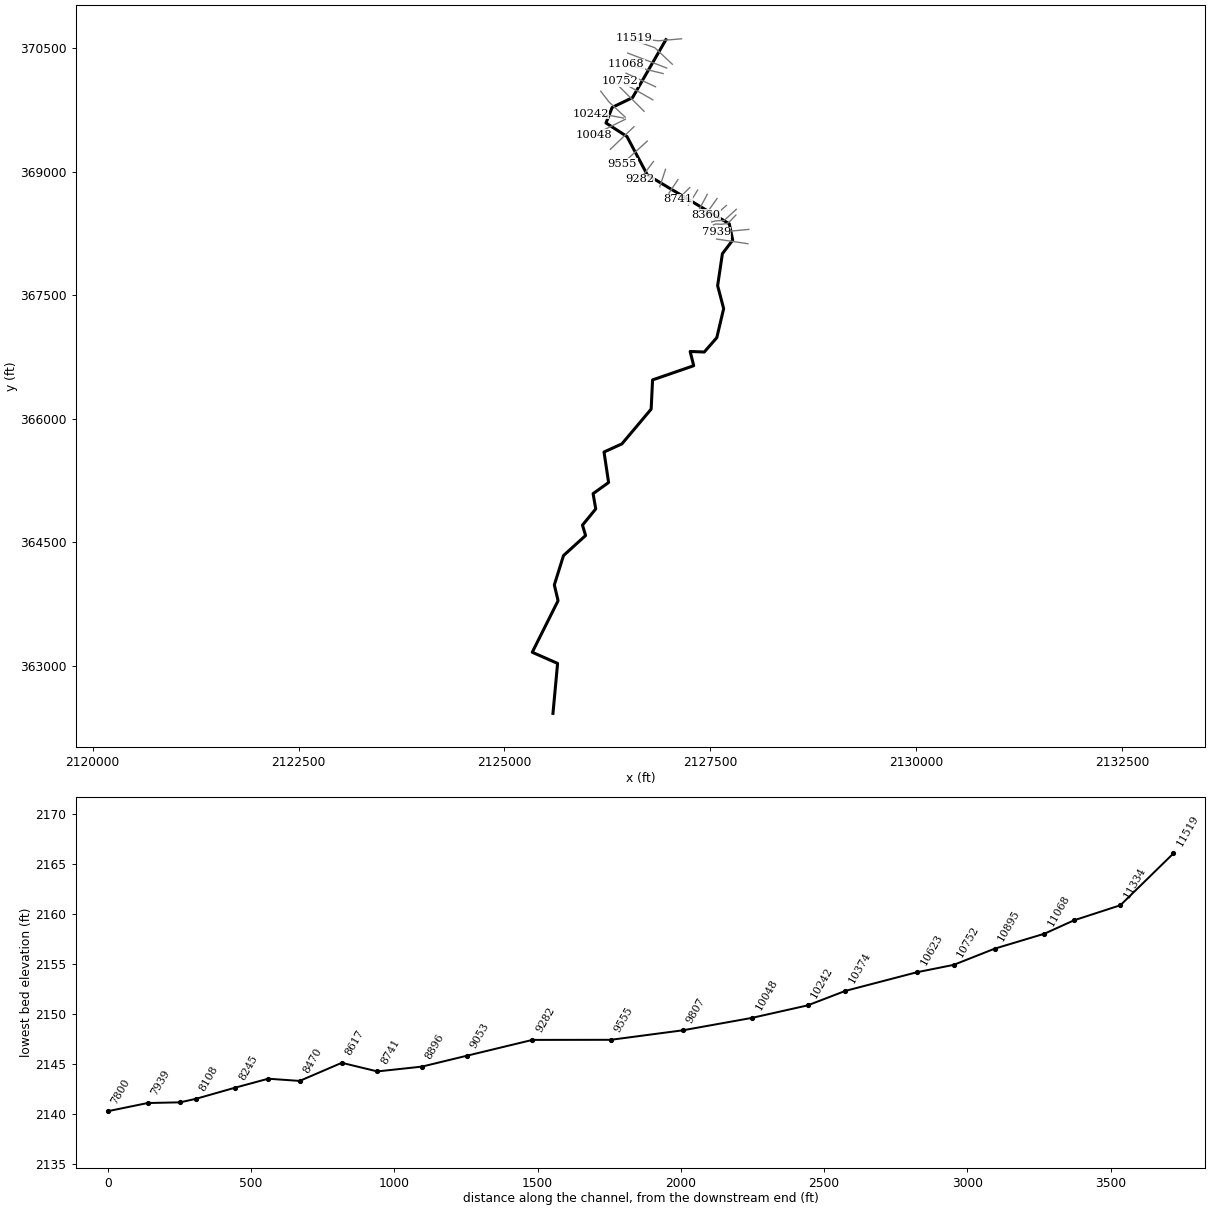
--- INDIANCK.prj (project) ---

Proj Title=INDIANCK
Current Plan=p01
Default Exp/Contr=0.3,0.1
English Units
Geom File=g01
Flow File=f01
Plan File=p01
Y Axis Title=Elevation
X Axis Title(PF)=Main Channel Distance
X Axis Title(XS)=Station
BEGIN DESCRIPTION:
Stream Name- Indian Creek
Flood Zone: Zone A
Greenbrier County, WV
County-Wide Study
WVDHSEM-2018-3, Flood Risk Project
HEC-RAS Version: 5.0.7
General Notes:
For the Hydrology Regression was used.
END DESCRIPTION:
DSS Export Rating Curves= 0
DSS Export Rating Curve Sorted= 0
DSS Export Volume Flow Curves= 0
DXF Filename=INDIANCK.G2.
DXF OffsetX= 0
DXF OffsetY= 0
DXF ScaleX= 1
DXF ScaleY= 10

--- INDIANCK.p01 (plan) ---

Plan Title=Floodplain
Program Version=5.07
Short Identifier=Floodplain
Geom File=g01
Flow File=f01
Subcritical Flow
K Sum by GR= 0
Std Step Tol= 0.01
Critical Tol= 0.01
Num of Std Step Trials= 20
Max Error Tol= 0.3
Flow Tol Ratio= 0.001
Split Flow NTrial= 30
Split Flow Tol= 0.02
Split Flow Ratio= 0.02
Log Output Level= 0
Friction Slope Method= 1
Unsteady Friction Slope Method= 2
Unsteady Bridges Friction Slope Method= 1
Parabolic Critical Depth
Global Vel Dist= 0 , 0 , 0
Global Log Level= 0
CheckData=True
Encroach Param=-1 ,0,0, 0
Computation Interval=1MIN
Output Interval=1HOUR
Instantaneous Interval=1HOUR
Mapping Interval=1HOUR
Computation Time Step Use Courant=        0
Computation Time Step Use Time Series=    0
Computation Time Step Count To Double=0
Computation Time Step Max Doubling=0
Computation Time Step Max Halving=0
Computation Time Step Residence Courant=0
Run HTab= 0
Run UNet= 0
Run Sediment= 0
Run PostProcess= 0
Run WQNet= 0
Run RASMapper= 0
UNET Theta= 1
UNET Theta Warmup= 1
UNET ZTol= 0.02
UNET ZSATol= 0.02
UNET MxIter= 20
UNET Max Iter WO Improvement= 0
UNET MaxInSteps= 0
UNET DtIC= 0
UNET DtMin= 0
UNET MaxCRTS= 20
UNET WFStab= 2
UNET SFStab= 1
UNET WFX= 1
UNET SFX= 1
UNET 1D Methodology=Finite Difference
UNET DSS MLevel= 4
UNET Pardiso=0
UNET DZMax Abort= 100
UNET Use Existing IB Tables=-1
UNET Froude Reduction=False
UNET Froude Limit= 0.8
UNET Froude Power= 4
UNET D1 Cores= 0
UNET D2 Coriolis=0
UNET D2 Cores= 0
UNET D2 Theta= 1
UNET D2 Theta Warmup= 1
UNET D2 Z Tol= 0.01
UNET D2 Volume Tol= 0.01
UNET D2 Max Iterations= 20
UNET D2 Equation= 0
UNET D2 RampUpFraction=0.1
UNET D2 TimeSlices= 1
UNET D2 BCVolumeCheck=0
UNET D1D2 MaxIter= 0
UNET D1D2 ZTol=0.01
UNET D1D2 QTol=0.1
UNET D1D2 MinQTol=1
Write IC File= 0
Write IC File at Fixed DateTime=0
Write IC File at Sim End=0
Echo Input=False
Echo Parameters=False
Echo Output=False
Write Detailed= 0
HDF Write Warmup=0
HDF Write Time Slices=0
HDF Flush=0
HDF Face Node Velocities=0
HDF Compression= 1
HDF Chunk Size= 1
HDF Spatial Parts= 1
HDF Use Max Rows=0
HDF Fixed Rows= 1
Calibration Method= 0
Calibration Iterations= 20
Calibration Max Change=0.05
Calibration Tolerance=0.2
Calibration Maximum=1.5
Calibration Minimum=0.5
Calibration Optimization Method= 1
WQ AD Non Conservative
WQ ULTIMATE=-1
WQ Max Comp Step=1HOUR
WQ Output Interval=15MIN
WQ Output Selected Increments= 0
WQ Output face flow=0
WQ Output face velocity=0
WQ Output face area=0
WQ Output face dispersion=0
WQ Output cell volume=0
WQ Output cell surface area=0
WQ Output cell continuity=0
WQ Output cumulative cell continuity=0
WQ Output face conc=0
WQ Output face dconc_dx=0
WQ Output face courant=0
WQ Output face peclet=0
WQ Output face adv mass=0
WQ Output face disp mass=0
WQ Output cell mass=0
WQ Output cell source sink temp=0
WQ Output nsm pathways=0
WQ Output nsm derived pathways=0
WQ Output MaxMinRange=-1
WQ Daily Max Min Mean=-1
WQ Daily Range=0
WQ Daily Time=0
WQ Create Restart=0
WQ Fixed Restart=0
WQ System Summary=0
WQ Write To DSS=0
WQ Use Fixed Temperature=0
Sorting and Armoring Iterations= 10
XS Update Threshold= 0.02
Bed Roughness Predictor= 0
Hydraulics Update Threshold= 0.02
Energy Slope Method= 1
Volume Change Method= 1
Sediment Retention Method= 0
XS Weighting Method= 0
Number of US Weighted Cross Sections= 1
Number of DS Weighted Cross Sections= 1
Upstream XS Weight=0
Main XS Weight=1
Downstream XS Weight=0
Number of DS XS's Weighted with US Boundary= 1
Upstream Boundary Weight= 1
Weight of XSs Associated with US Boundary= 0
Number of US XS's Weighted with DS Boundary= 1
Downstream Boundary Weight= 0.5
Weight of XSs Associated with DS Boundary= 0.5
Percentile Method= 0
Sediment Output Level= 3
Mass or Volume Output= 0
Output Increment Type= 1
Profile and TS Output Increment= 1
XS Output Flag= 0
XS Output Increment= 10
Write Gradation File= 0
Read Gradation Hotstart= 0
Write HDF5 File= 1
Write Binary Output= 1
Write DSS Sediment File= 0
SV Curve= 0
Specific Gage Flag= 0

--- INDIANCK.f01 (steady flow) ---

Flow Title=Flow
Program Version=5.07
Number of Profiles= 6
Profile Names=f1p,f10p,f4p,f2p,f02p,f1pplus
River Rch & RM=BURNSRN,Main            ,9203
     572     302     402     484     799     846
River Rch & RM=BURNSRN,Main            ,7195
     649     345     457     550     905     960
River Rch & RM=BURNSRN,Main            ,4526
    1220     661     867    1040    1670    1800
River Rch & RM=BURNSRNT1,Main            ,2875
     504     265     353     426     705     745
River Rch & RM=BURNSRNT1,Main            ,2198
     669     356     472     568     932     990
River Rch & RM=CLBRSNCKT1,Main            ,2948
     116    57.4    78.7    96.5     166     171
River Rch & RM=CLBRSNCKT1,Main            ,2280
     138    69.1    94.4     116     198     210
River Rch & RM=CLBRSNCKT1,Main            ,1216
     156    78.2     107     130     223     230
River Rch & RM=CLBRSNCKT1,Main            ,243
     178    89.6     122     149     253     300
River Rch & RM=CLBRSNCKT2,Main            ,5369
     223     114     154     187     317     330
River Rch & RM=CLBRSNCKT2,Main            ,3799
     483     253     338     408     676     714
River Rch & RM=INDIANCK,Main            ,11519
     313     162     218     264     443     463
River Rch & RM=INDIANCK,Main            ,9807
     520     274     365     440     728     769
River Rch & RM=INDIANCK,Main            ,8108
     581     307     409     492     812     860
River Rch & RM=INDIANCK,Main            ,6227
     647     344     456     549     902     958
River Rch & RM=LTROARCK,Main            ,4000
     648     344     456     549     903     958
River Rch & RM=MLGNCKTR5,Main            ,7678
     581     307     409     492     812     860
River Rch & RM=MLGNCKTR5,Main            ,5118
     654     347     461     554     911     967
River Rch & RM=MLGNCKTR5,Main            ,2636
     728     388     514     617    1010    1080
River Rch & RM=ROARINGCK,Main            ,17918
     544     287     382     461     761     805
River Rch & RM=ROARINGCK,Main            ,16996
     613     325     431     519     855     906
River Rch & RM=ROARINGCK,Main            ,14906
     713     380     504     605     992    1060
River Rch & RM=ROARINGCK,Main            ,11661
     864     464     612     734    1200    1280
River Rch & RM=ROARINGCK,Main            ,8657
     964     520     685     820    1330    1430
River Rch & RM=ROARINGCK,Main            ,4987
    1570     861    1120    1340    2150    2320
Boundary for River Rch & Prof#=BURNSRN,Main            , 1
Up Type= 0
Dn Type= 3
Dn Slope=0.0012
Boundary for River Rch & Prof#=BURNSRN,Main            , 2
Up Type= 0
Dn Type= 3
Dn Slope=0.0012
Boundary for River Rch & Prof#=BURNSRN,Main            , 3
Up Type= 0
Dn Type= 3
Dn Slope=0.0012
Boundary for River Rch & Prof#=BURNSRN,Main            , 4
Up Type= 0
Dn Type= 3
Dn Slope=0.0012
Boundary for River Rch & Prof#=BURNSRN,Main            , 5
Up Type= 0
Dn Type= 3
Dn Slope=0.0012
Boundary for River Rch & Prof#=BURNSRN,Main            , 6
Up Type= 0
Dn Type= 3
Dn Slope=0.0012
Boundary for River Rch & Prof#=BURNSRNT1,Main            , 1
Up Type= 0
Dn Type= 3
Dn Slope=0.00496
Boundary for River Rch & Prof#=BURNSRNT1,Main            , 2
Up Type= 0
Dn Type= 3
Dn Slope=0.00496
Boundary for River Rch & Prof#=BURNSRNT1,Main            , 3
Up Type= 0
Dn Type= 3
Dn Slope=0.00496
Boundary for River Rch & Prof#=BURNSRNT1,Main            , 4
Up Type= 0
Dn Type= 3
Dn Slope=0.00496
Boundary for River Rch & Prof#=BURNSRNT1,Main            , 5
Up Type= 0
Dn Type= 3
Dn Slope=0.00496
Boundary for River Rch & Prof#=BURNSRNT1,Main            , 6
Up Type= 0
Dn Type= 3
Dn Slope=0.00496
Boundary for River Rch & Prof#=CLBRSNCKT1,Main            , 1
Up Type= 0
Dn Type= 3
Dn Slope=0.00848
Boundary for River Rch & Prof#=CLBRSNCKT1,Main            , 2
Up Type= 0
Dn Type= 3
Dn Slope=0.00848
Boundary for River Rch & Prof#=CLBRSNCKT1,Main            , 3
Up Type= 0
Dn Type= 3
Dn Slope=0.00848
Boundary for River Rch & Prof#=CLBRSNCKT1,Main            , 4
Up Type= 0
Dn Type= 3
Dn Slope=0.00848
Boundary for River Rch & Prof#=CLBRSNCKT1,Main            , 5
Up Type= 0
Dn Type= 3
Dn Slope=0.00848
Boundary for River Rch & Prof#=CLBRSNCKT1,Main            , 6
Up Type= 0
Dn Type= 3
Dn Slope=0.00848
Boundary for River Rch & Prof#=CLBRSNCKT2,Main            , 1
Up Type= 0
Dn Type= 3
Dn Slope=0.00274
Boundary for River Rch & Prof#=CLBRSNCKT2,Main            , 2
Up Type= 0
Dn Type= 3
Dn Slope=0.00274
Boundary for River Rch & Prof#=CLBRSNCKT2,Main            , 3
Up Type= 0
Dn Type= 3
Dn Slope=0.00274
Boundary for River Rch & Prof#=CLBRSNCKT2,Main            , 4
Up Type= 0
Dn Type= 3
Dn Slope=0.00274
Boundary for River Rch & Prof#=CLBRSNCKT2,Main            , 5
Up Type= 0
Dn Type= 3
Dn Slope=0.00274
Boundary for River Rch & Prof#=CLBRSNCKT2,Main            , 6
Up Type= 0
Dn Type= 3
Dn Slope=0.00274
Boundary for River Rch & Prof#=INDIANCK,Main            , 1
Up Type= 0
Dn Type= 3
Dn Slope=0.00176
Boundary for River Rch & Prof#=INDIANCK,Main            , 2
Up Type= 0
Dn Type= 3
Dn Slope=0.00176
Boundary for River Rch & Prof#=INDIANCK,Main            , 3
Up Type= 0
Dn Type= 3
Dn Slope=0.00176
Boundary for River Rch & Prof#=INDIANCK,Main            , 4
Up Type= 0
Dn Type= 3
Dn Slope=0.00176
Boundary for River Rch & Prof#=INDIANCK,Main            , 5
Up Type= 0
Dn Type= 3
Dn Slope=0.00176
Boundary for River Rch & Prof#=INDIANCK,Main            , 6
Up Type= 0
Dn Type= 3
Dn Slope=0.00176
Boundary for River Rch & Prof#=LTROARCK,Main            , 1
Up Type= 0
Dn Type= 3
Dn Slope=0.04436
Boundary for River Rch & Prof#=LTROARCK,Main            , 2
Up Type= 0
Dn Type= 3
Dn Slope=0.04436
Boundary for River Rch & Prof#=LTROARCK,Main            , 3
Up Type= 0
Dn Type= 3
Dn Slope=0.04436
Boundary for River Rch & Prof#=LTROARCK,Main            , 4
Up Type= 0
Dn Type= 3
Dn Slope=0.04436
Boundary for River Rch & Prof#=LTROARCK,Main            , 5
Up Type= 0
Dn Type= 3
Dn Slope=0.04436
Boundary for River Rch & Prof#=LTROARCK,Main            , 6
Up Type= 0
Dn Type= 3
Dn Slope=0.04436
Boundary for River Rch & Prof#=MLGNCKTR5,Main            , 1
Up Type= 0
Dn Type= 3
Dn Slope=0.0247
Boundary for River Rch & Prof#=MLGNCKTR5,Main            , 2
Up Type= 0
Dn Type= 3
Dn Slope=0.0247
Boundary for River Rch & Prof#=MLGNCKTR5,Main            , 3
Up Type= 0
Dn Type= 3
Dn Slope=0.0247
Boundary for River Rch & Prof#=MLGNCKTR5,Main            , 4
Up Type= 0
Dn Type= 3
Dn Slope=0.0247
Boundary for River Rch & Prof#=MLGNCKTR5,Main            , 5
Up Type= 0
Dn Type= 3
Dn Slope=0.0247
Boundary for River Rch & Prof#=MLGNCKTR5,Main            , 6
Up Type= 0
Dn Type= 3
Dn Slope=0.0247
Boundary for River Rch & Prof#=ROARINGCK,Main            , 1
Up Type= 0
Dn Type= 3
Dn Slope=0.01435
Boundary for River Rch & Prof#=ROARINGCK,Main            , 2
Up Type= 0
Dn Type= 3
Dn Slope=0.01435
Boundary for River Rch & Prof#=ROARINGCK,Main            , 3
Up Type= 0
Dn Type= 3
Dn Slope=0.01435
Boundary for River Rch & Prof#=ROARINGCK,Main            , 4
Up Type= 0
Dn Type= 3
Dn Slope=0.01435
Boundary for River Rch & Prof#=ROARINGCK,Main            , 5
Up Type= 0
Dn Type= 3
Dn Slope=0.01435
Boundary for River Rch & Prof#=ROARINGCK,Main            , 6
Up Type= 0
Dn Type= 3
Dn Slope=0.01435
DSS Import GetInterval= 0
DSS Import GetPeak= 0
DSS Import FillOption= 0

--- INDIANCK.g01 (geometry) ---

Geom Title=Geometry
Program Version=5.07

River Reach=INDIANCK        ,Main
Reach XY= 30
2126960.91899589370606.1859758652126555.01626438369901.671964943
2126308.14143005369782.921874359 2126232.7941398369594.033144534
2126487.30806646369429.7969244422126735.57200563368962.088542283
2127730.71076337368367.9913052772127771.68312237368170.074706361
2127646.68304428368005.144261941 2127588.6969398367616.602716193
2127661.96090087367337.7830638592127578.62740612 366985.00522612
2127426.54404888366810.3526882832127255.01650479366817.296900108
2127298.41897705366644.0331390352126798.76643303366471.463602275
 2126781.4052473366116.2553232012126426.54408038365694.380510777
2126209.18296653365595.074935108 2126264.7386297365224.588799447
2126076.54412422365089.5191877042126108.48861411364903.408011362
2125947.72482803364706.8805172892125985.22475305  364580.1442222
 2125717.1691868364336.7414937762125605.71074829 363980.14410986
2125651.19687778363788.4774984422125337.65518203363161.741547197
2125645.29400247363026.3248232752125589.21734297362419.014358118

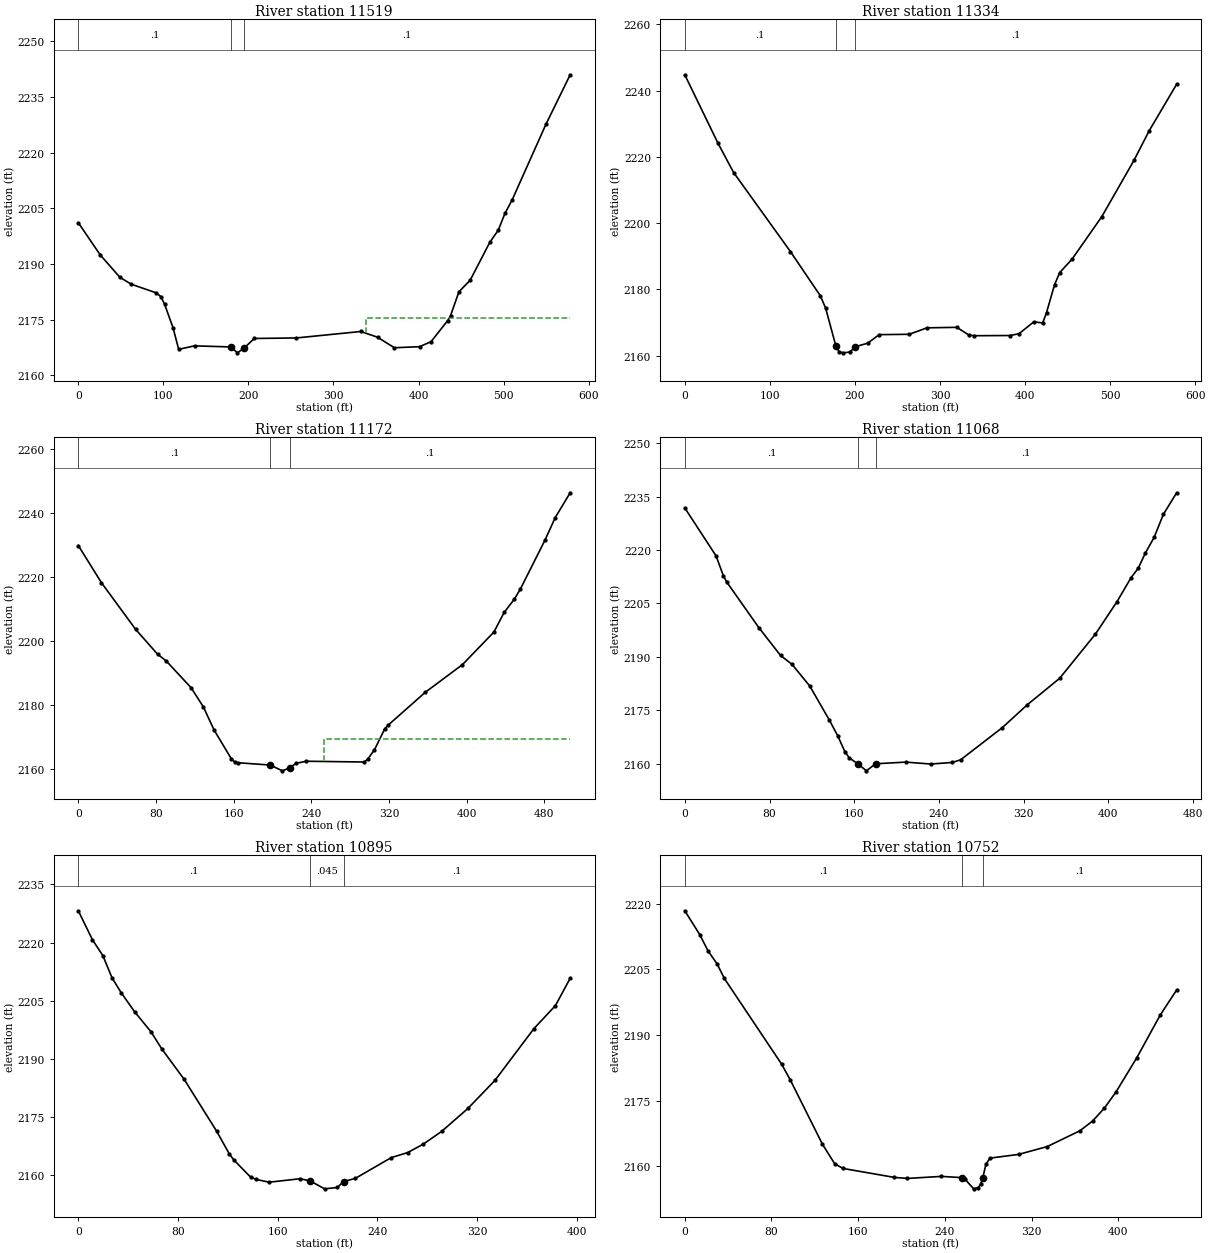
Type RM Length L Ch R = 1 ,11519   ,193.8,185.1,178.1
XS GIS Cut Line= 3
 2127150.2624492 370616.902817952126869.70690796370592.597420365
2126574.56806254 370622.45858112
#Sta/Elev= 30
       0  2201.1    25.7 2192.44    48.8 2186.41      62 2184.55    91.6  2182.2
    97.2 2181.15   101.5 2179.09   111.4 2172.77     118 2166.98   136.6 2167.92
  179.342167.633   187.1 2166.04  195.062167.354   206.9 2169.91   256.3 2170.05
   332.1 2171.79   351.8 2170.25   371.6 2167.41   401.3  2167.7   414.8 2169.06
   434.3 2174.74   437.6 2176.03   447.5 2182.48   460.7 2185.59   483.9 2195.85
   493.7 2199.06   501.6 2203.59   510.1 2207.25   549.9 2227.66   578.3 2240.95
#Mann= 3 ,-1 , 0
       0      .1       0  179.34    .045       0  195.06      .1       0
#XS Ineff= 1 ,-1
   338.2  578.25 2175.49
Permanent Ineff=
       F
Bank Sta=179.34,195.06
XS Rating Curve= 0 ,0
Exp/Cntr=0.3,0.1

Type RM Length L Ch R = 1 ,11334   ,158,162.1,165.5
XS GIS Cut Line= 3
2127038.45689854370307.8752207762126824.91533089370508.916813448
2126556.16521221370603.708290532
#Sta/Elev= 30
       0  2244.8    38.7 2224.31    57.4  2215.3   124.2 2191.44   159.4 2178.07
   165.6 2174.35  177.592162.974   181.6 2161.14   186.4 2160.86   194.2  2161.1
  200.432162.699   215.1 2163.78   228.6 2166.35   263.9 2166.46   284.8 2168.41
   319.9 2168.56   333.8 2166.26   340.4 2166.03   382.5 2166.09     393 2166.64
   410.4 2170.22   420.8 2169.88   425.3    2173   434.7 2181.37   440.7 2185.04
   455.6 2189.23   490.4 2202.01   528.2 2218.99     546 2227.89   578.3 2241.94
#Mann= 3 ,-1 , 0
       0      .1       0  177.59    .045       0  200.43      .1       0
Bank Sta=177.59,200.43
XS Rating Curve= 0 ,0
Exp/Cntr=0.3,0.1

Type RM Length L Ch R = 1 ,11172   ,101.4,103.3,104.3
XS GIS Cut Line= 3
2126969.70670795370262.0416510252126722.83187363370356.833456203
2126496.79033095370443.291944698
#Sta/Elev= 30
       0 2229.77    23.8 2218.18      59 2203.58    81.6 2195.82    90.7 2193.65
   116.1 2185.35   128.8 2179.33   139.8 2172.12   157.4  2163.2   160.9 2162.13
     164 2161.89  197.732161.156   210.1 2159.35  217.732160.293   224.2  2161.7
   234.7 2162.35   294.4 2162.11     298    2163     305 2165.95   315.5 2172.44
     319 2173.62   357.3 2183.91   395.5 2192.54   427.9 2202.71   438.5 2208.87
     449 2213.02   455.1 2216.11   480.6 2231.49   491.1 2238.51   506.5 2246.28
#Mann= 3 ,-1 , 0
       0      .1       0  197.73    .045       0  217.73      .1       0
#XS Ineff= 1 ,-1
  252.63  506.46 2169.25
Permanent Ineff=
       F
Bank Sta=197.73,217.73
XS Rating Curve= 0 ,0
Exp/Cntr=0.3,0.1

Type RM Length L Ch R = 1 ,11068   ,167.9,173.2,169.4
XS GIS Cut Line= 2
2126926.99846005370194.333453119 2126475.9567112370304.750227034
#Sta/Elev= 30
       0 2231.82    29.6 2218.32    36.4 2212.79    39.7 2210.97    70.1 2198.14
    90.4 2190.41   101.3 2187.89   118.1 2181.78   136.6  2172.2   144.5  2167.8
   151.2 2163.35   155.5 2161.59  163.51 2159.97   171.5 2158.01  180.162159.996
   208.6 2160.46   232.3 2159.92   252.5 2160.37   260.4  2161.1   299.8 2170.14
   323.5 2176.59   353.9 2183.97   387.7 2196.39     408 2205.46   421.4 2212.25
   428.2 2214.91   434.9 2219.18   443.2 2223.57   451.8 2229.98   464.4 2236.07
#Mann= 3 ,-1 , 0
       0      .1       0  163.51    .045       0  180.16      .1       0
Bank Sta=163.51,180.16
XS Rating Curve= 0 ,0
Exp/Cntr=0.3,0.1

Type RM Length L Ch R = 1 ,10895   ,144.1,143.1,141.2
XS GIS Cut Line= 2
2126834.29031211370033.916779205 2126475.9567112370199.541776031
#Sta/Elev= 30
       0 2228.18    11.3 2220.73    19.7 2216.62    27.1 2210.87    34.5 2207.02
    45.2 2202.14    58.3 2197.01    66.9 2192.63      85 2184.72   111.1 2171.34
   121.1 2165.57   124.7    2164   138.3 2159.54   142.8 2158.94   153.2 2158.23
   177.9 2159.12  185.962158.579   197.7 2156.52   207.9 2156.87  212.862158.397
   222.4 2159.22   251.2 2164.57   264.4 2165.87   276.8 2168.02   291.6 2171.31
   312.7 2177.23   334.4 2184.46   365.7 2197.81     383 2203.75   394.8 2210.79
#Mann= 3 ,-1 , 0
       0      .1       0  185.96    .045       0  212.86      .1       0
Bank Sta=185.96,212.86
XS Rating Curve= 0 ,0
Exp/Cntr=0.3,0.1

Type RM Length L Ch R = 1 ,10752   ,128.6,128.8,123.9
XS GIS Cut Line= 2
2126801.99838197369875.5834344482126407.20684871370099.541647956
#Sta/Elev= 30
       0 2218.36    13.8 2212.93    21.4 2209.22    29.8 2206.26    36.5 2202.91
    89.3 2183.38    97.2 2179.83     127  2165.1   138.3 2160.64   145.9 2159.56
   193.4 2157.51   205.5 2157.28   236.8 2157.74  255.732157.459   258.4 2157.14
   266.6  2154.9   270.7 2155.19   272.9  2155.9  274.962157.383   277.9 2160.49
   281.6 2161.91   308.1 2162.76   334.5 2164.55   364.6 2168.15   376.4 2170.38
   387.3 2173.35     398 2177.03     417 2184.76   438.9 2194.62   453.9 2200.28
#Mann= 3 ,-1 , 0
       0      .1       0  255.73    .045       0  274.96      .1       0
Bank Sta=255.73,274.96
XS Rating Curve= 0 ,0
Exp/Cntr=0.3,0.1

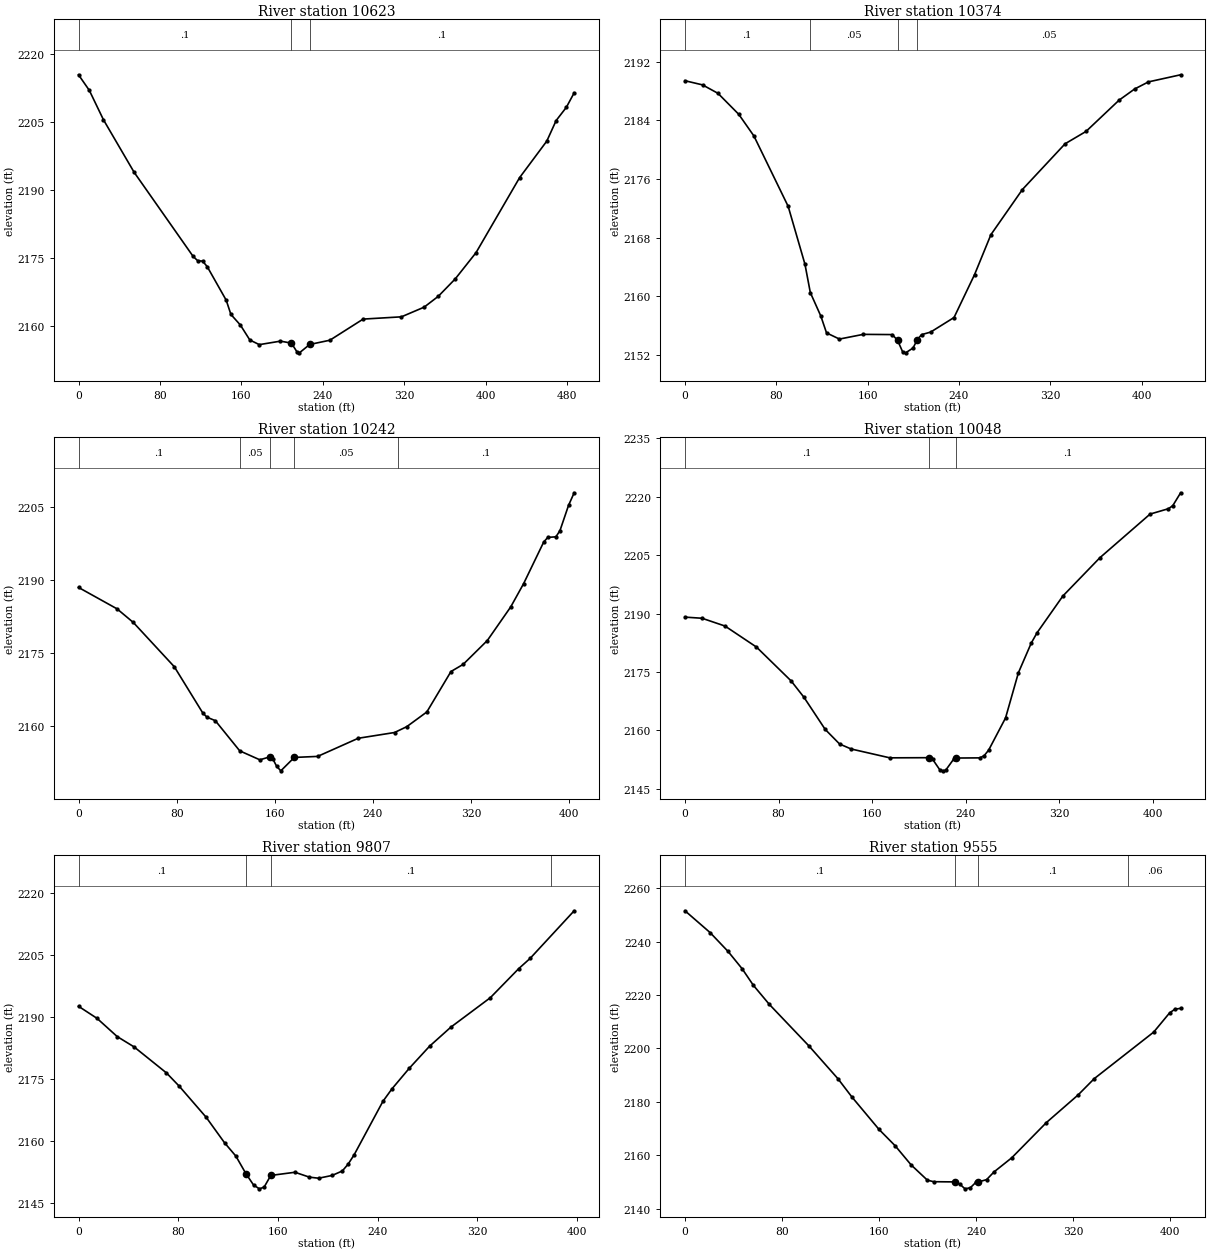
Type RM Length L Ch R = 1 ,10623   ,247.3,249,246.8
XS GIS Cut Line= 2
2126695.74859446369736.0000521992126350.95696121370079.750020862
#Sta/Elev= 30
       0 2215.47    10.6 2212.04    24.5 2205.55    54.6 2193.98   112.6 2175.42
   117.1 2174.47   121.9 2174.38   126.4 2173.18   145.1 2165.76   149.7 2162.63
     159 2160.29   168.3 2156.99   177.6 2155.97   198.4 2156.74  209.132156.302
   214.9 2154.27     217 2154.16  227.092156.007   246.9 2156.94   279.6  2161.6
   317.2  2162.1   339.5 2164.23   353.4 2166.62   370.1 2170.47   390.5 2176.25
   433.3 2192.79     460 2200.84   469.2 2205.38   479.2 2208.29   486.9 2211.49
#Mann= 3 ,-1 , 0
       0      .1       0  209.13    .045       0  227.09      .1       0
Bank Sta=209.13,227.09
XS Rating Curve= 0 ,0
Exp/Cntr=0.3,0.1

Type RM Length L Ch R = 1 ,10374   ,124.3,131.9,134.1
XS GIS Cut Line= 3
2126466.58172995369665.1668605362126268.66513103369850.583484456
  2126169.086735369979.629276895
#Sta/Elev= 30
       0 2189.42    15.4 2188.85    28.9  2187.7    47.1 2184.84    60.4 2181.88
    90.4 2172.28   105.1 2164.39   109.8 2160.52     119 2157.32     124 2155.02
   135.3 2154.18   156.2 2154.82   181.6 2154.79  186.252154.001   190.8 2152.39
   193.3  2152.3   199.8 2152.96  203.51  2154.1   207.2 2154.78   215.2 2155.13
   235.7 2157.12   253.7 2162.98     268 2168.42   295.6 2174.58     333 2180.82
   351.3  2182.5   380.3 2186.77   393.9 2188.29     406 2189.26   434.2 2190.23
#Mann= 4 ,-1 , 0
       0      .1       0  109.12     .05       0  186.25    .045       0
  203.51     .05       0
Bank Sta=186.25,203.51
XS Rating Curve= 0 ,0
Exp/Cntr=0.3,0.1

Type RM Length L Ch R = 1 ,10242   ,180.5,194.4,194.3
XS GIS Cut Line= 3
2126446.79010287 369653.70855011 2126239.4985227369692.250139698
 2126046.7902467369704.750114694
#Sta/Elev= 30
       0 2188.46    31.4 2184.07    44.7 2181.27    78.1 2172.19   101.4 2162.67
   104.8 2161.84   111.5 2161.14   131.4 2154.95   147.8 2153.11  155.892153.717
   158.2 2153.38   161.5 2151.78   164.9 2150.85  175.892153.599   194.9 2153.81
     228 2157.53   257.6 2158.71   267.5  2159.9   283.9 2162.92   303.6 2171.22
   313.5 2172.68   333.2 2177.57   352.3 2184.47   362.8 2189.24   379.2 2197.78
   382.5 2198.72   389.1 2198.84   392.4 2200.09   399.4 2205.28     404 2207.87
#Mann= 5 ,-1 , 0
       0      .1       0  131.59     .05       0  155.89    .045       0
  175.89     .05       0  260.57      .1       0
Bank Sta=155.89,175.89
XS Rating Curve= 0 ,0
Exp/Cntr=0.3,0.1

Type RM Length L Ch R = 1 ,10048   ,236.1,240.9,244.1
XS GIS Cut Line= 2
2126467.62339455369639.1252459442126088.45683005369450.583300203
#Sta/Elev= 30
       0 2189.07    14.6 2188.78    34.2 2186.78    61.1 2181.38    90.7 2172.69
   101.7 2168.47   119.8 2160.24   132.1 2156.49     142 2155.21     175 2152.94
  208.732152.978   211.6 2152.56   217.7 2149.87   220.2  2149.6   222.7 2149.74
   229.9 2152.74  231.272152.887   251.9 2152.93   255.6 2153.48   259.5 2154.94
   273.9 2163.18   284.9  2174.8   295.9 2182.43   300.9 2185.09   322.9  2194.5
   354.5 2204.32   397.4 2215.53   413.1 2216.91   416.8  2217.7   423.5    2221
#Mann= 3 ,-1 , 0
       0      .1       0  208.73    .045       0  231.27      .1       0
Bank Sta=208.73,231.27
XS Rating Curve= 0 ,0
Exp/Cntr=0.3,0.1

Type RM Length L Ch R = 1 ,9807    ,253,251.3,252.1
XS GIS Cut Line= 2
2126572.83184555369548.5000991232126285.33176437369273.499992952
#Sta/Elev= 30
       0 2192.54    14.9 2189.61      31 2185.22    44.6 2182.71    70.6 2176.41
    80.9 2173.18   102.5 2165.66   117.2 2159.51   126.3 2156.28   134.32152.066
   140.5 2149.28   145.2 2148.36     149 2148.79  154.312151.605   173.7 2152.37
   185.3 2151.19   192.7 2150.93   203.5  2151.6   211.7 2152.68   216.4 2154.34
   221.2 2156.59   244.3 2169.53   251.6 2172.57   265.5 2177.55   281.7 2182.86
   298.8 2187.48   330.5 2194.61   353.3 2201.65   362.4 2204.11   397.8 2215.65
#Mann= 4 ,-1 , 0
       0      .1       0   134.3    .045       0  154.31      .1       0
   379.3     .06       0
Bank Sta=134.3,154.31
XS Rating Curve= 0 ,0
Exp/Cntr=0.3,0.1

Type RM Length L Ch R = 1 ,9555    ,267.8,273.6,274.4
XS GIS Cut Line= 2
2126734.29018405369373.500121027 2126432.2067987369098.500014871
#Sta/Elev= 30
       0 2251.53    20.7 2243.37    35.5 2236.31    47.1 2229.83    56.4  2223.6
    69.5 2216.49   102.2  2200.9   126.1 2188.63   137.4  2181.9   159.9 2169.67
   173.2 2163.55   186.4 2156.36   199.8 2150.65     205 2150.08  222.232150.008
   226.4  2149.2   230.8 2147.41   235.2 2147.83   239.7 2149.83  241.84 2149.99
   248.6 2150.86   254.7 2153.75   269.3 2159.03   297.9 2172.24     324 2182.57
   337.3 2188.67   386.3  2206.1   399.4 2213.29   403.9 2214.71   408.5 2214.98
#Mann= 4 ,-1 , 0
       0      .1       0  222.23    .045       0  241.84      .1       0
  365.29     .06       0
Bank Sta=222.23,241.84
XS Rating Curve= 0 ,0
Exp/Cntr=0.3,0.1

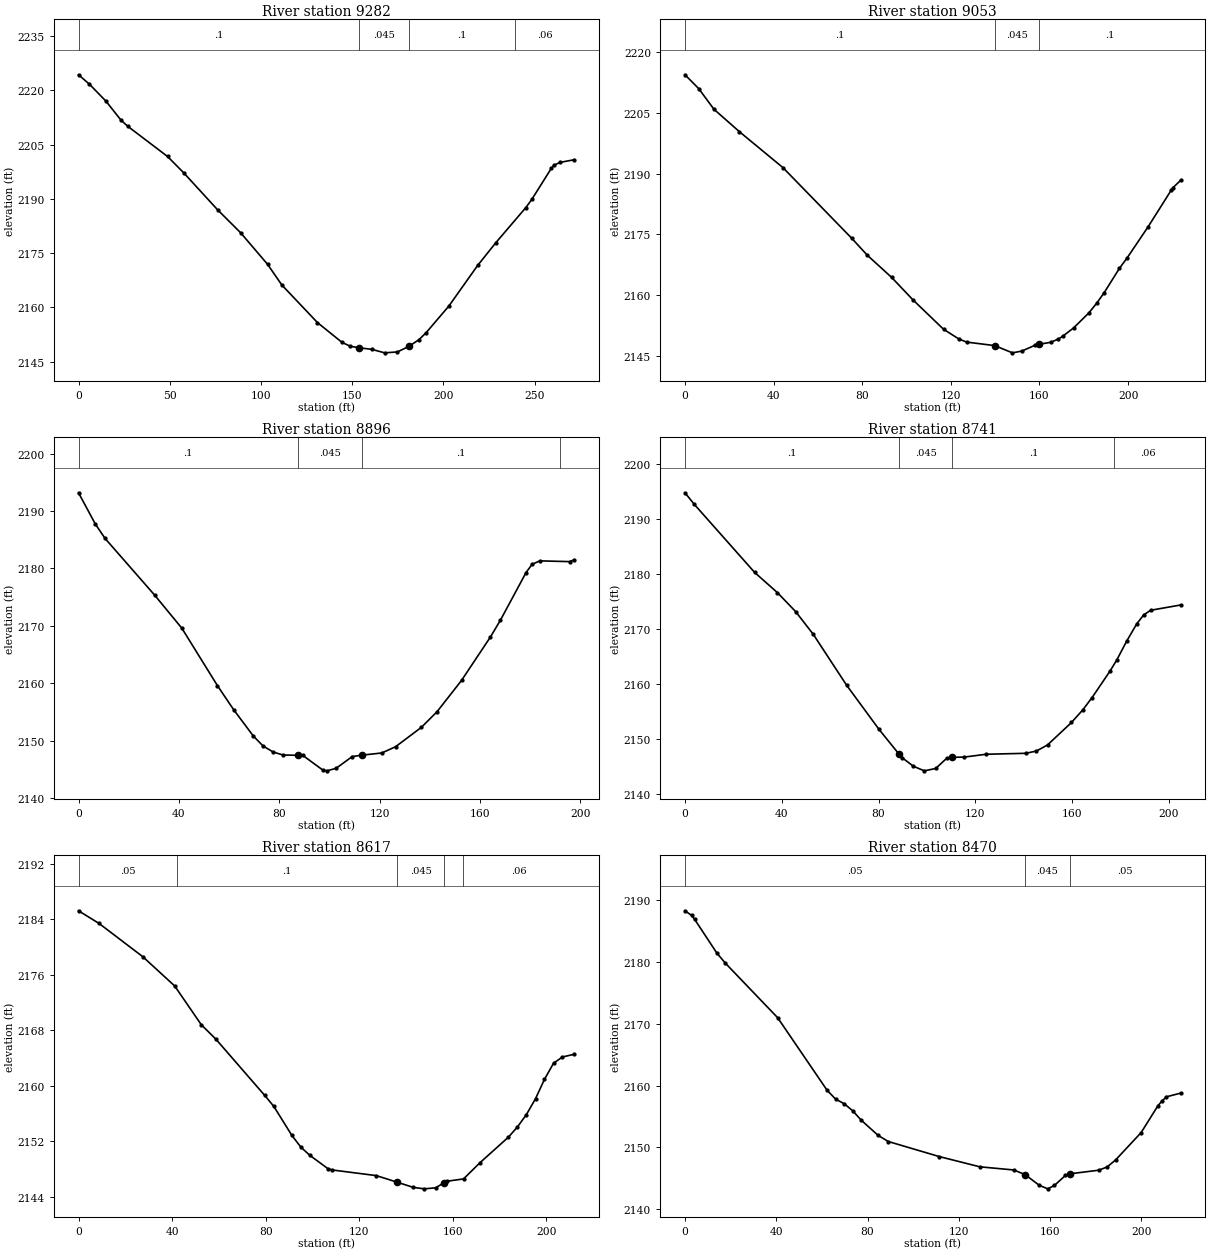
Type RM Length L Ch R = 1 ,9282    ,223.9,228.6,231.7
XS GIS Cut Line= 2
2126809.29003406369125.5832940342126646.79003096368907.875068039
#Sta/Elev= 30
       0 2224.31       6  2221.7    15.1 2216.98    23.3 2211.75    27.1 2210.02
    48.8 2201.71    57.6 2197.23    76.2 2186.99    88.8 2180.65   103.6 2171.91
   111.5 2166.14     131 2155.76   144.4 2150.31     149 2149.22  153.842148.803
   160.8 2148.36   167.8  2147.4   174.8 2147.65  181.122149.188   186.6 2151.03
   190.5 2152.94     203 2160.33   218.8 2171.58   228.7 2177.83   245.2 2187.57
   248.5 2189.85   259.2 2198.45   260.7  2199.3   263.9 2200.07   271.7 2200.81
#Mann= 4 ,-1 , 0
       0      .1       0  153.84    .045       0  181.12      .1       0
  239.31     .06       0
Bank Sta=153.84,181.12
XS Rating Curve= 0 ,0
Exp/Cntr=0.3,0.1

Type RM Length L Ch R = 1 ,9053    ,160.4,157,154.2
XS GIS Cut Line= 2
2126956.16506839 369030.79181695 2126886.3735413368818.291913867
#Sta/Elev= 30
       0 2214.34     6.2 2210.93    13.1 2205.83    24.6  2200.3    44.2 2191.47
    75.3 2174.03    82.2 2169.92    93.3 2164.39   102.9 2158.87   116.7 2151.63
   123.6 2149.24   127.1 2148.47  139.742147.609   147.8 2145.82     152 2146.25
   158.1 2147.72  159.762147.924   165.1 2148.42   168.5 2149.22   170.4 2149.87
   175.4 2151.96   182.3 2155.67   185.8 2158.04   189.2 2160.65   196.1 2166.66
   199.6 2169.25   209.1 2176.95   219.5 2185.94   220.3 2186.55   223.7 2188.33
#Mann= 3 ,-1 , 0
       0      .1       0  139.74    .045       0  159.76      .1       0
Bank Sta=139.74,159.76
XS Rating Curve= 0 ,0
Exp/Cntr=0.3,0.1

Type RM Length L Ch R = 1 ,8896    ,157,155.6,152.6
XS GIS Cut Line= 2
2127107.20676103368905.7917388682126997.83197978368741.208406612
#Sta/Elev= 30
       0 2193.16     6.7 2187.72    10.6  2185.2    30.3 2175.36    41.2 2169.57
    55.4 2159.56    61.8 2155.41    69.7 2150.79    73.6 2149.05    77.6 2148.01
    81.5 2147.49   87.472147.435    89.4 2147.42    97.3  2144.9      99 2144.73
   102.7 2145.17   109.1 2147.21  113.212147.475   120.9 2147.84   126.4 2148.93
   136.7 2152.31   142.9 2155.01   152.7 2160.48   164.2 2168.03   168.2 2170.97
   178.4 2179.25   180.8 2180.69   183.9  2181.3   195.8 2181.17   197.6 2181.48
#Mann= 4 ,-1 , 0
       0      .1       0   87.47    .045       0  113.21      .1       0
  191.88     .06       0
Bank Sta=87.47,113.21
XS Rating Curve= 0 ,0
Exp/Cntr=0.3,0.1

Type RM Length L Ch R = 1 ,8741    ,121.5,124.2,126.3
XS GIS Cut Line= 2
2127250.95680162368808.9169326132127105.12343186368665.166892037
#Sta/Elev= 30
       0 2194.85     3.9 2192.72    28.8 2180.35    38.2 2176.68    45.7 2173.24
      53  2169.1    66.8 2159.82    80.2 2151.78    88.42147.314    89.7 2146.65
    94.4 2145.08    98.9 2144.25   103.6 2144.68   108.3  2146.6  110.51 2146.71
   115.3 2146.75   124.5 2147.27   140.8 2147.44   145.2 2147.85   149.8 2148.96
   159.7 2153.05   164.4 2155.36   168.2 2157.58   175.6 2162.39   178.4 2164.41
   182.5 2167.85   186.6 2170.95   189.5 2172.61   192.4 2173.47   204.8 2174.43
#Mann= 4 ,-1 , 0
       0      .1       0    88.4    .045       0  110.51      .1       0
  177.39     .06       0
Bank Sta=88.4,110.51
XS Rating Curve= 0 ,0
Exp/Cntr=0.3,0.1

Type RM Length L Ch R = 1 ,8617    ,145,147,145.8
XS GIS Cut Line= 2
 2127345.7486068368777.6666670292127234.29016829368597.458366036
#Sta/Elev= 30
       0 2185.22     8.8 2183.39    27.5 2178.59    41.1 2174.38    52.5 2168.78
    58.7 2166.71    79.6 2158.59    83.5    2157    91.2 2152.82    95.1 2151.11
    98.9 2149.94   106.6 2148.03   108.5 2147.83   127.3 2147.02  136.212146.073
   143.1 2145.32   147.9 2145.11   152.7 2145.26  156.212145.976   157.4  2146.2
   164.6 2146.54   171.7  2148.9   183.8 2152.57   187.6 2154.02   191.5 2155.83
   195.4 2158.13   199.2  2160.9   203.1 2163.24   206.9 2164.13   211.9 2164.52
#Mann= 5 ,-1 , 0
       0     .05       0   41.93      .1       0  136.21    .045       0
  156.21      .1       0  164.28     .06       0
Bank Sta=136.21,156.21
XS Rating Curve= 0 ,0
Exp/Cntr=0.3,0.1

Type RM Length L Ch R = 1 ,8470    ,112.1,109.6,108.6
XS GIS Cut Line= 2
2127462.41504014 368725.583437862127360.33191097368533.916826442
#Sta/Elev= 30
       0 2188.25     2.9  2187.5     4.2 2186.88      14  2181.4    17.7 2179.78
    40.6 2170.97    62.3 2159.22      66 2157.81    69.8 2157.05    73.5 2155.92
    77.2 2154.41    84.6 2151.95    89.1 2150.95   111.4 2148.52   129.2 2146.86
   144.1 2146.35  149.092145.587   155.3 2143.86     159  2143.3   161.9 2143.85
   166.7 2145.46  168.542145.726   181.3 2146.31     185 2146.84   188.7 2147.97
   199.9  2152.4   207.3 2156.76   209.1 2157.52     211 2158.18   217.2 2158.77
#Mann= 3 ,-1 , 0
       0     .05       0  149.09    .045       0  168.54     .05       0
Bank Sta=149.09,168.54
XS Rating Curve= 0 ,0
Exp/Cntr=0.3,0.1

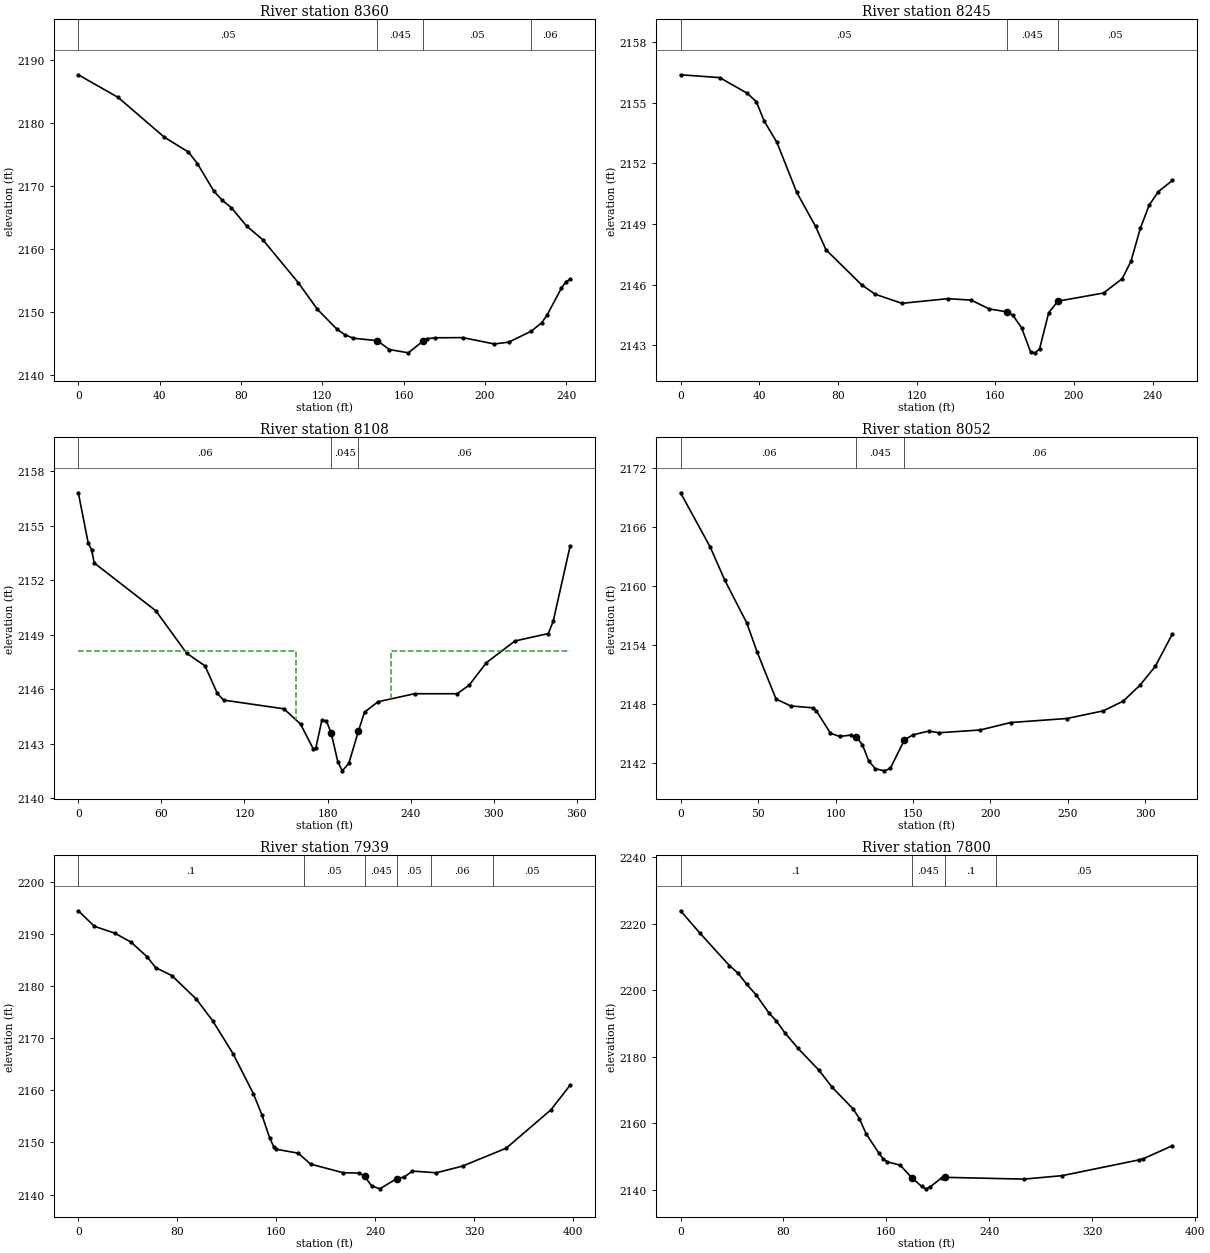
Type RM Length L Ch R = 1 ,8360    ,115.1,114.9,111.2
XS GIS Cut Line= 2
2127582.20679531368675.5835378622127441.58174846368478.708603531
#Sta/Elev= 30
       0  2187.7    19.6  2184.1    42.3 2177.78    54.1 2175.44    58.6 2173.58
    66.6 2169.24    70.7 2167.78    75.3 2166.57    82.8 2163.66    90.8 2161.47
   108.2 2154.66   117.6 2150.43   127.1 2147.31   131.1  2146.4   135.2 2145.85
  147.132145.447   152.9 2144.05   162.3 2143.52  169.472145.363   171.5 2145.76
   175.5 2145.91     189 2145.94   204.6 2144.93   211.7 2145.22   222.8 2146.96
   227.9  2148.3   230.5 2149.49   237.6  2153.8   239.9 2154.84   241.9 2155.19
#Mann= 4 ,-1 , 0
       0     .05       0  147.13    .045       0  169.47     .05       0
  222.43     .06       0
Bank Sta=147.13,169.47
XS Rating Curve= 0 ,0
Exp/Cntr=0.3,0.1

Type RM Length L Ch R = 1 ,8245    ,134.6,137.5,130
XS GIS Cut Line= 4
2127694.70689836368591.2083785382127613.45673278368520.375186861
2127524.91524321 368430.791704612127512.41526821368420.375058785
#Sta/Elev= 30
       0 2156.39    19.9 2156.25    33.8 2155.48    38.5 2155.06    42.5  2154.1
      49 2153.04      59 2150.58    68.6 2148.89    73.9 2147.73      92    2146
    98.9 2145.53   112.5 2145.08   135.8 2145.31   147.7 2145.24     157  2144.8
  165.822144.661   168.8  2144.5   173.3 2143.88     178 2142.65   180.2 2142.63
   182.5 2142.83   187.1 2144.61  191.762145.186     215 2145.59   224.5  2146.3
   228.9 2147.15   233.7 2148.79   238.2 2149.94   242.9 2150.61     250 2151.16
#Mann= 3 ,-1 , 0
       0     .05       0  165.82    .045       0  191.76     .05       0
Bank Sta=165.82,191.76
XS Rating Curve= 0 ,0
Exp/Cntr=0.5,0.3

Type RM Length L Ch R = 1 ,8108    ,56.7,55.2,54.6
XS GIS Cut Line= 6
2127815.54031813368544.3334722822127730.61299455368466.750622198
2127663.59934905368405.6395239532127630.85630429 368408.09489961
2127557.86990172368403.8239107882127516.58192655368390.166785866
#Sta/Elev= 30
       0  2156.8     7.1 2154.05     9.6 2153.66    11.5 2152.94      56 2150.31
    78.2 2147.98    91.5 2147.28   100.4 2145.77   104.9  2145.4   148.5 2144.92
   160.5 2144.08   169.8  2142.7   171.5 2142.76   175.9 2144.29   179.1 2144.26
   182.6 2143.59   187.5 2141.98   190.7 2141.51   195.4 2141.93   202.3  2143.7
   206.7 2144.74   216.5 2145.31   242.8 2145.75   273.6 2145.75   282.3 2146.22
   294.6 2147.45   315.3 2148.65   339.5 2149.06     343 2149.75   355.2 2153.88
#Mann= 3 , 0 , 0
       0     .06       0   182.6    .045       0   202.3     .06       0
#XS Ineff= 2 ,-1
       0  156.96  2148.1  225.72  355.16  2148.1
Permanent Ineff=
       F       F
Bank Sta=182.6,202.3
XS Rating Curve= 0 ,0
Exp/Cntr=0.5,0.3

Type RM Length L Ch R = 1 ,8052    ,122.9,113.4,104
XS GIS Cut Line= 6
2127810.33199522368474.5419452042127736.02965039368397.174645871
2127704.77971289368371.7580300272127633.56463221368362.764937788
2127569.32854021368366.584483951 2127537.4152182 368355.79185462
#Sta/Elev= 30
       0 2169.48    19.2 2163.93    28.5 2160.59    42.7 2156.23    49.3 2153.31
    61.6 2148.47    71.1 2147.77    85.3 2147.58    87.6 2147.28    96.7 2144.99
   102.7 2144.66   109.7  2144.8  113.472144.605   117.3 2143.83   121.5 2142.14
   125.7 2141.38   131.5 2141.16   135.3  2141.4  144.452144.299   149.8 2144.82
   160.2 2145.21   166.9 2145.04   193.3 2145.32   213.1 2146.08   249.3 2146.49
   272.8 2147.27   285.6 2148.25   296.4 2149.87   306.4 2151.81   317.4 2155.11
#Mann= 3 ,-1 , 0
       0     .06       0  113.47    .045       0  144.45     .06       0
Bank Sta=113.47,144.45
XS Rating Curve= 0 ,0
Exp/Cntr=0.5,0.3

Type RM Length L Ch R = 1 ,7939    ,141.4,139.4,133.8
XS GIS Cut Line= 2
2127967.62367538368300.5833036152127571.79014945368263.083378613
#Sta/Elev= 30
       0 2194.51      13 2191.52    29.5 2190.21    42.7 2188.47    55.9  2185.6
    62.5 2183.59    75.6 2182.06    95.4 2177.54   108.6 2173.38   125.1 2167.05
   141.5 2159.38   148.3 2155.37   154.7 2150.86     158 2149.16   160.1 2148.69
   177.8 2147.94   187.7 2145.85     214 2144.19   227.2 2144.11  231.392143.509
   237.1 2141.67   243.7 2141.09  257.47 2143.06   263.5 2143.37   270.1  2144.5
   289.5 2144.18   310.6 2145.46   345.9  2148.9   382.1 2156.28   397.6 2161.02
#Mann= 6 ,-1 , 0
       0      .1       0  182.37     .05       0  231.39    .045       0
  257.47     .05       0  285.03     .06       0   335.1     .05       0
Bank Sta=231.39,257.47
XS Rating Curve= 0 ,0
Exp/Cntr=0.3,0.1

Type RM Length L Ch R = 1 ,7800    ,198.6,203.9,191.9
XS GIS Cut Line= 2
2127956.16503689368126.6249901212127578.04013696368182.875205696
#Sta/Elev= 30
       0 2223.83    14.8 2217.22      38 2207.34    44.6 2205.13    51.3 2201.78
    58.5 2198.67    68.8 2193.08    74.5  2190.7    81.1 2187.15    91.1 2182.57
   107.7 2175.86   117.6  2170.9   134.2 2164.25     139 2161.37   144.2 2156.85
   154.1 2151.03   157.4 2149.35   160.7 2148.39   170.7 2147.39  179.572143.672
   187.3 2141.02   190.6 2140.27   193.9 2140.81   202.9 2143.57  205.852143.726
   266.9 2143.19   296.7 2144.24   356.4 2148.97   359.8 2149.34   382.3 2153.24
#Mann= 4 ,-1 , 0
       0      .1       0  179.57    .045       0  205.85      .1       0
   245.4     .05       0
Bank Sta=179.57,205.85
XS Rating Curve= 0 ,0
Exp/Cntr=0.3,0.1