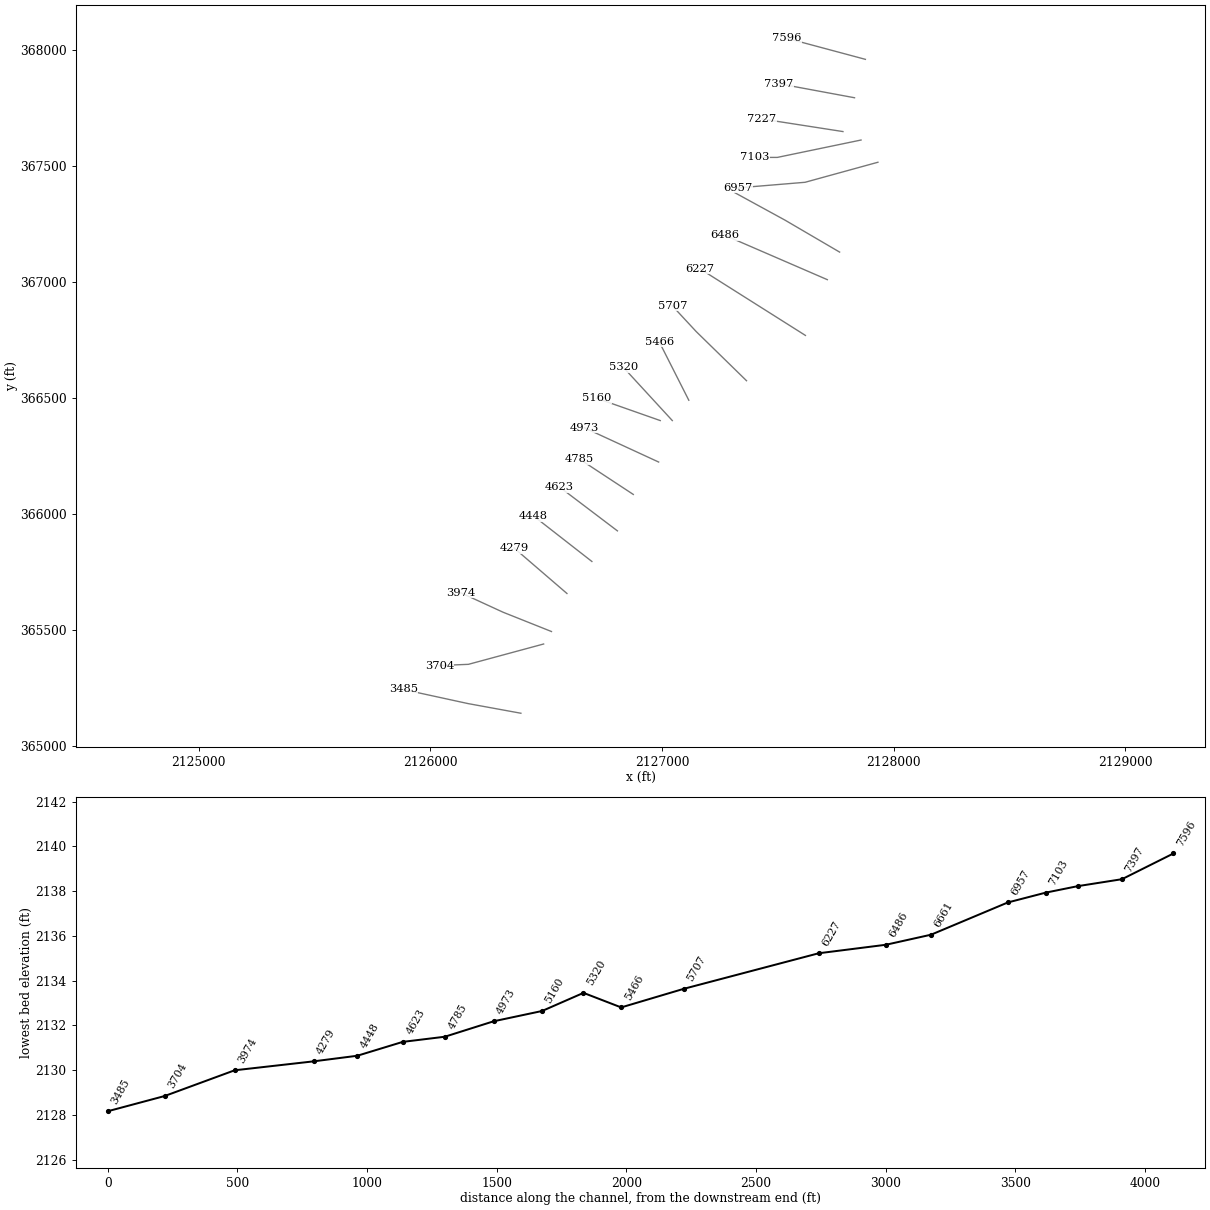
HEC-RAS study INDIANCK.prj: INDIANCK

--- INDIANCK.g01 (geometry) --- (continued)

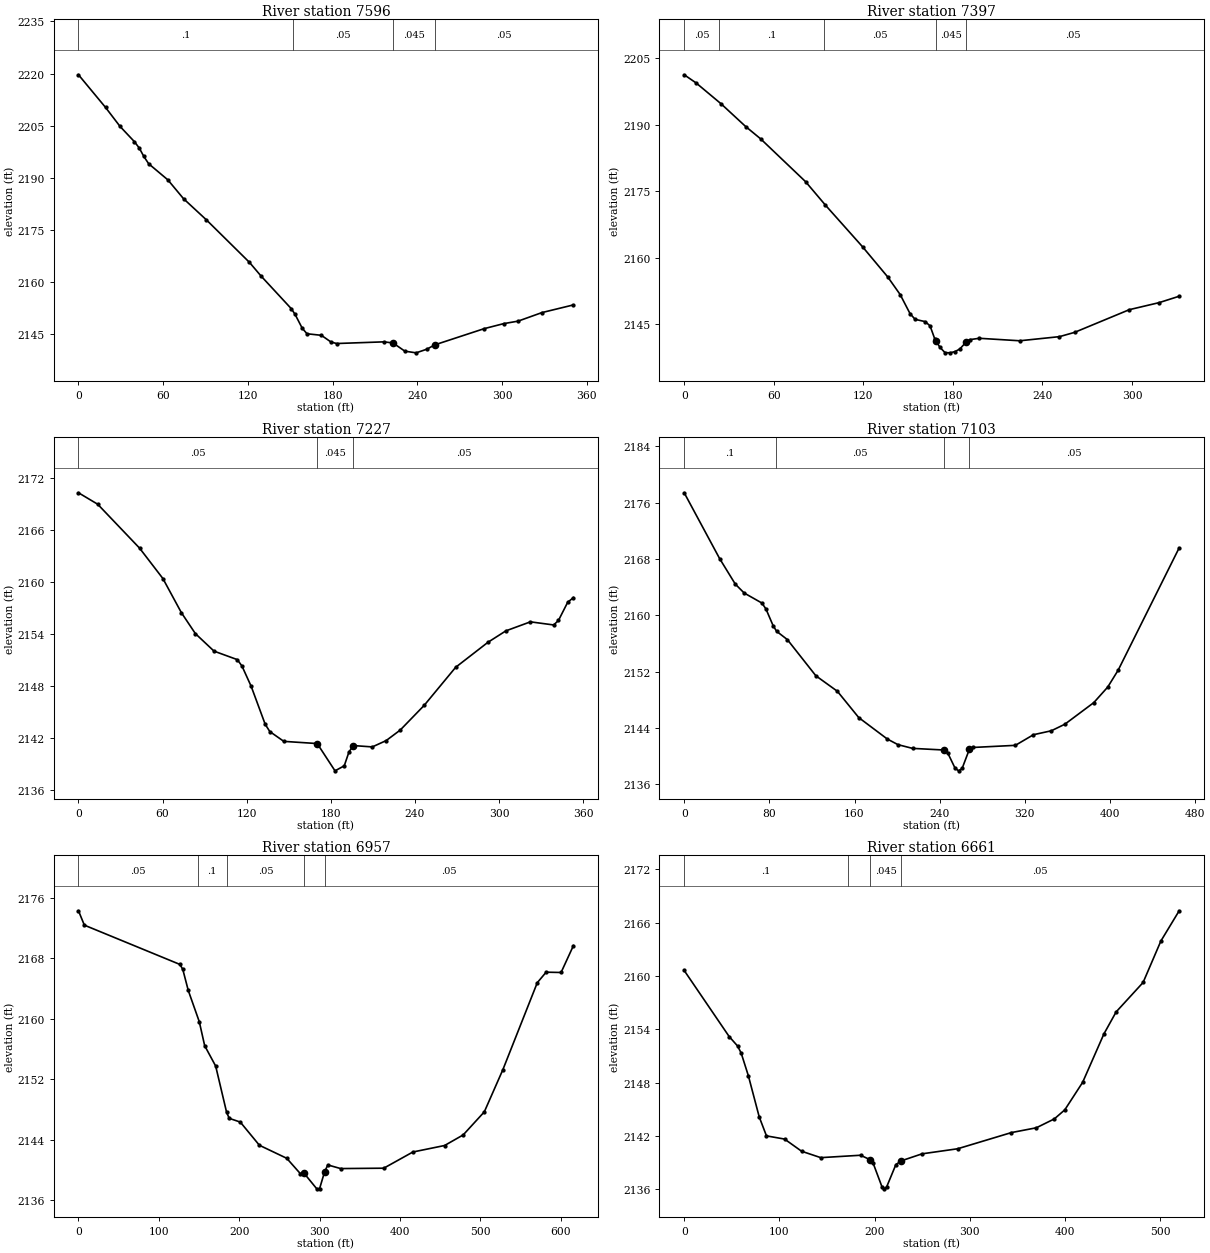
Type RM Length L Ch R = 1 ,7596    ,196.8,198.6,201.1
XS GIS Cut Line= 2
2127878.04019314367959.9583286942127539.49854738 368050.58347553
#Sta/Elev= 30
       0 2219.66    19.2 2210.25    29.4 2204.82    39.6 2200.42      43 2198.61
    46.3 2196.16    49.7 2194.07    63.3 2189.43    74.4 2184.01    90.5 2177.96
   121.1 2165.69   129.2 2161.81   150.7 2152.38   153.4 2150.73   158.4 2146.79
   161.8 2145.17     172 2144.72   178.8  2142.8   182.8 2142.36   216.2 2142.84
  222.712142.526   231.1 2140.16   239.1 2139.68   246.7 2140.73   252.22141.962
   287.3 2146.64   301.1 2148.08   311.3  2148.8   328.2 2151.26   350.5 2153.47
#Mann= 4 ,-1 , 0
       0      .1       0  151.78     .05       0  222.71    .045       0
   252.2     .05       0
Bank Sta=222.71,252.2
XS Rating Curve= 0 ,0
Exp/Cntr=0.3,0.1

Type RM Length L Ch R = 1 ,7397    ,167.9,170.2,168.7
XS GIS Cut Line= 2
2127831.16528687367794.3333318682127505.12361613367854.750205785
#Sta/Elev= 30
       0 2201.21     7.9 2199.39    24.6  2194.7    41.2 2189.54    51.2 2186.77
    81.3 2177.12    94.6 2171.83   119.5 2162.43   136.4 2155.62   144.7 2151.66
   151.3 2147.37   154.7 2146.08   161.4 2145.57   164.7 2144.62     168 2141.54
  168.682141.194   171.4 2139.74   174.7 2138.59     178 2138.53   181.5 2138.82
   184.7 2139.41  188.932140.987   191.4 2141.51   197.7 2141.81   224.8 2141.25
   251.4 2142.18   261.5 2143.14   298.2 2148.26   318.2 2149.85   331.6 2151.29
#Mann= 5 ,-1 , 0
       0     .05       0   23.52      .1       0   93.37     .05       0
  168.68    .045       0  188.93     .05       0
Bank Sta=168.68,188.93
XS Rating Curve= 0 ,0
Exp/Cntr=0.3,0.1

Type RM Length L Ch R = 1 ,7227    ,119.4,123.7,127.9
XS GIS Cut Line= 2
2127781.16505879367648.499962121 2127432.2067672367702.666848525
#Sta/Elev= 30
       0  2170.3    13.7 2168.98    43.6 2163.91    60.2 2160.41    73.4 2156.47
    83.4 2154.05    96.7 2152.03   113.3 2151.05   116.6 2150.32   123.2 2147.97
   133.2 2143.59   136.5 2142.75   146.5 2141.62  170.312141.367     183 2138.22
   189.6  2138.8     193 2140.42  196.192141.135   209.6 2140.98   219.5 2141.71
   229.5 2142.92   246.6 2145.77   269.1 2150.17   292.1 2153.05   304.9 2154.37
   322.4 2155.41     339 2155.05   342.4 2155.57     349 2157.67   353.1 2158.21
#Mann= 3 ,-1 , 0
       0     .05       0  170.31    .045       0  196.19     .05       0
Bank Sta=170.31,196.19
XS Rating Curve= 0 ,0
Exp/Cntr=0.3,0.1

Type RM Length L Ch R = 1 ,7103    ,141.9,146.5,143.7
XS GIS Cut Line= 3
2127859.29023063367612.0417017042127497.83196405367537.041851699
 2127401.9984943367537.041851699
#Sta/Elev= 30
       0 2177.42    33.3 2168.07      48 2164.45    56.3 2163.19      73 2161.76
    76.8 2160.92    83.5 2158.56    86.8 2157.75    96.9 2156.57   123.7 2151.43
   143.9 2149.23     164 2145.49   190.8 2142.45   200.8 2141.65   214.5 2141.12
  244.252140.886   247.8  2140.4   254.4 2138.33   257.8 2137.93   261.1 2138.27
  267.882140.976   271.2 2141.25   311.1 2141.55   328.1 2143.06   344.9 2143.62
   357.6 2144.55   384.8 2147.62   397.9 2149.83   407.7 2152.23     465  2169.6
#Mann= 4 ,-1 , 0
       0      .1       0   86.16     .05       0  244.25    .045       0
  267.88     .05       0
Bank Sta=244.25,267.88
XS Rating Curve= 0 ,0
Exp/Cntr=0.3,0.1

Type RM Length L Ch R = 1 ,6957    ,292.6,295.9,270.1
XS GIS Cut Line= 3
2127932.20675147367516.2085600352127617.62339112367429.750071526
2127329.08197346367405.791786119
#Sta/Elev= 30
       0 2174.26     7.3 2172.36   126.3 2167.16   129.8  2166.5   136.6 2163.72
   150.3 2159.59     157 2156.42   170.7 2153.72   184.3  2147.6   187.6 2146.81
   201.3 2146.32   225.1 2143.25   259.1 2141.53   276.1 2139.49  280.572139.563
   296.5 2137.49     300 2137.53  306.212139.748   310.2 2140.65   326.2 2140.17
   379.8 2140.22     416 2142.36   455.5 2143.22   478.6 2144.62   504.9 2147.67
     528 2153.25   570.8 2164.75   581.8 2166.14   600.4  2166.1   615.8 2169.66
#Mann= 5 ,-1 , 0
       0     .05       0  148.23      .1       0  184.52     .05       0
  280.57    .045       0  306.21     .05       0
Bank Sta=280.57,306.21
XS Rating Curve= 0 ,0
Exp/Cntr=0.3,0.1

Type RM Length L Ch R = 1 ,6661    ,171.9,174.3,173.7
XS GIS Cut Line= 3
2127766.75531071367128.7083507782127530.64423439367266.729400203
 2127314.4986693367384.784938365
#Sta/Elev= 30
       0 2160.62    47.2 2153.19      56 2152.13    59.8 2151.34    67.4 2148.77
    78.8 2144.14    86.4 2142.01   105.4 2141.65   123.3 2140.28   143.4 2139.56
   185.2 2139.83  195.352139.325   198.3 2138.97   207.9 2136.22   210.3 2136.05
   212.7 2136.29   222.3 2138.78  227.912139.201   249.8 2139.99   287.2 2140.56
   343.6 2142.38   369.8 2142.92   388.7 2143.92   399.7 2144.94   418.4 2148.03
   440.8 2153.49   453.6 2155.96   481.9 2159.27   500.6 2163.94   519.8 2167.34
#Mann= 4 ,-1 , 0
       0      .1       0  171.95     .05       0  195.35    .045       0
  227.91     .05       0
Bank Sta=195.35,227.91
XS Rating Curve= 0 ,0
Exp/Cntr=0.3,0.1

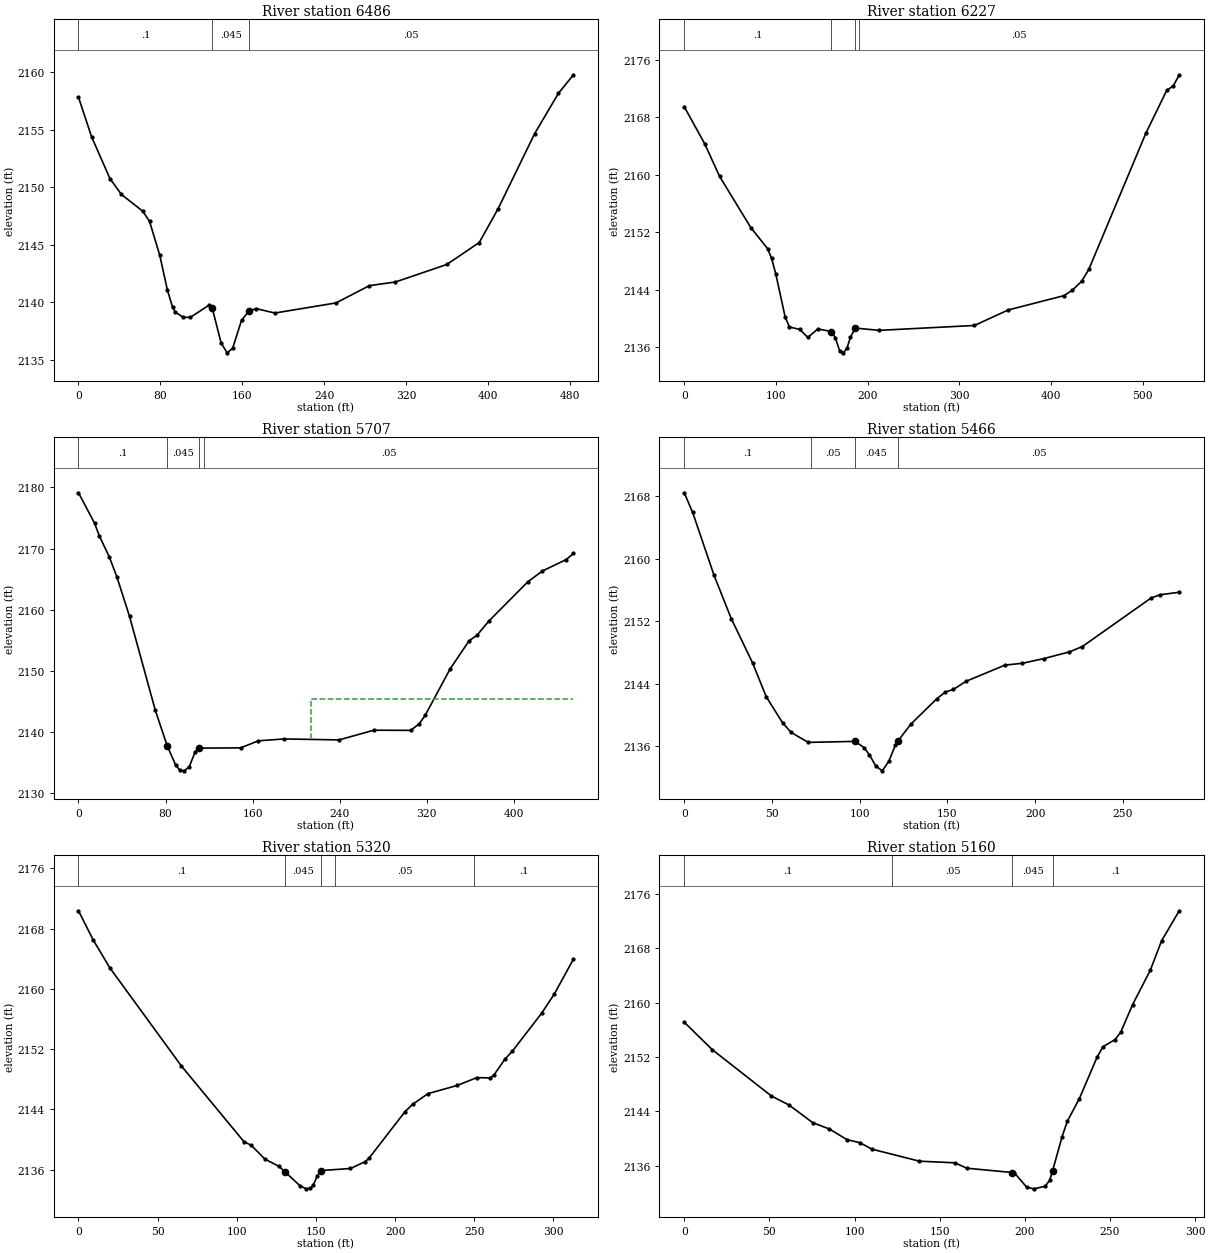
Type RM Length L Ch R = 1 ,6486    ,257.2,259.2,250.9
XS GIS Cut Line= 2
2127713.80397305367009.7847041192127270.22776046367201.625199705
#Sta/Elev= 30
       0 2157.82    12.8 2154.38    30.7 2150.75    41.9 2149.37    62.9  2147.9
    69.4 2147.02    79.3  2144.1    86.8 2141.07    91.8 2139.57    94.3 2139.16
   102.2 2138.69   109.3 2138.69   127.2 2139.73  130.622139.483   139.2 2136.48
   145.1  2135.6   150.5 2135.99   159.2 2138.43  166.542139.242   173.7 2139.44
   191.8 2139.06   251.5 2139.94     284 2141.44   309.5 2141.76   359.6 2143.28
   391.3 2145.19   409.6 2148.11   445.3 2154.64   468.6 2158.16   483.3 2159.77
#Mann= 3 ,-1 , 0
       0      .1       0  130.62    .045       0  166.54     .05       0
Bank Sta=130.62,166.54
XS Rating Curve= 0 ,0
Exp/Cntr=0.3,0.1

Type RM Length L Ch R = 1 ,6227    ,499.6,520.8,493
XS GIS Cut Line= 2
2127619.18605205366769.3334133632127162.58886811367057.528046951
#Sta/Elev= 30
       0 2169.48    22.3 2164.33    38.6 2159.77    72.7 2152.64      91 2149.71
    95.3 2148.36    99.9 2146.18     110 2140.24   114.7 2138.82     126 2138.48
   134.8 2137.36   145.7 2138.55  160.352138.189   164.7 2137.35   169.7 2135.42
   173.6 2135.22   177.5 2135.88   181.3  2137.4  186.532138.668   212.4 2138.35
   316.5 2139.03   353.4 2141.19   414.1 2143.18   423.4 2143.95   433.5 2145.19
   441.3 2146.85   503.4 2165.77   526.2 2171.75   533.4 2172.39   539.9 2173.93
#Mann= 4 ,-1 , 0
       0      .1       0  160.35    .045       0  186.53      .1       0
  190.13     .05       0
Bank Sta=160.35,186.53
XS Rating Curve= 0 ,0
Exp/Cntr=0.3,0.1

Type RM Length L Ch R = 1 ,5707    ,244.9,241,233.8
XS GIS Cut Line= 3
2127364.84568146366574.0208118712127147.83200789366785.826490611
2127044.53332996366896.937488869
#Sta/Elev= 30
       0 2179.13    14.8 2174.15    19.1  2172.1    28.5 2168.57    35.4 2165.31
    46.9 2158.92    70.6 2143.55   81.522137.744    89.4 2134.54    93.4  2133.7
    97.3 2133.63   101.9 2134.34   107.3 2136.75  110.86 2137.35   149.1 2137.39
   165.3 2138.54     189 2138.85   239.4 2138.69   271.5 2140.28   305.4 2140.25
   313.3 2141.35   318.8 2142.75   341.7 2150.34   359.1 2154.92   366.3 2155.81
     377  2158.1   412.9 2164.54   426.3 2166.32   448.2 2168.19     455  2169.2
#Mann= 4 ,-1 , 0
       0      .1       0   81.52    .045       0  110.86      .1       0
  115.54     .05       0
#XS Ineff= 1 ,-1
  213.92  454.95 2145.39
Permanent Ineff=
       F
Bank Sta=81.52,110.86
XS Rating Curve= 0 ,0
Exp/Cntr=0.3,0.1

Type RM Length L Ch R = 1 ,5466    ,141.3,145.4,147.9
XS GIS Cut Line= 2
2127115.71363381366489.8195367012126988.10955828366741.555581778
#Sta/Elev= 30
       0 2168.47     4.8 2165.95      17 2157.88    26.8 2152.33      39 2146.63
    46.7 2142.33    56.1 2138.95      61 2137.72    70.7 2136.45   97.322136.579
   102.5 2135.79   105.5 2134.88   109.2 2133.42   112.9  2132.8   116.6 2134.01
   120.3 2136.06  121.642136.572   129.3 2138.82     144 2142.05   148.9 2142.91
   153.4 2143.24   160.7 2144.29   182.8 2146.36   192.8  2146.6     205  2147.2
   219.6 2148.06     227 2148.75     266 2154.95   271.1 2155.38   282.2 2155.71
#Mann= 4 ,-1 , 0
       0      .1       0   72.53     .05       0   97.32    .045       0
  121.64     .05       0
Bank Sta=97.32,121.64
XS Rating Curve= 0 ,0
Exp/Cntr=0.3,0.1

Type RM Length L Ch R = 1 ,5320    ,154,159.8,161.8
XS GIS Cut Line= 2
2127044.53332996366402.1458275322126832.72765121366632.180800527
#Sta/Elev= 30
       0 2170.36     9.3 2166.49    19.7 2162.82      65 2149.76   104.5 2139.72
   109.2 2139.22   117.8 2137.39   126.7 2136.43  130.292135.747   140.1 2133.82
     144 2133.45   146.3 2133.51   148.2 2133.91   150.9 2135.17  153.092135.878
   171.8 2136.15   181.1 2137.06   183.5 2137.51   206.3  2143.7   211.1 2144.67
   220.8 2146.09   239.2 2147.17   251.6 2148.21   260.1 2148.18   262.4 2148.54
   269.4 2150.67     274  2151.7   292.6 2156.77   300.7 2159.35   312.7 2163.96
#Mann= 5 ,-1 , 0
       0      .1       0  130.29    .045       0  153.09      .1       0
  162.21     .05       0  249.93      .1       0
Bank Sta=130.29,153.09
XS Rating Curve= 0 ,0
Exp/Cntr=0.3,0.1

Type RM Length L Ch R = 1 ,5160    ,183.7,186.9,179.9
XS GIS Cut Line= 2
2126992.44977272366402.1458275322126718.14421895366498.499965534
#Sta/Elev= 30
       0 2157.11    16.4 2153.09    51.2 2146.27    61.6 2144.94    75.5 2142.35
    85.3 2141.42    95.6 2139.86   103.1 2139.42   110.3 2138.46   138.1  2136.7
     159 2136.46   165.9 2135.67  192.742135.037   193.8 2135.03   201.1 2132.88
   205.3 2132.64     212 2133.02   214.6  2133.9  216.342135.315   221.9  2140.3
     225 2142.58     232 2145.87   242.4 2151.95   245.9 2153.51   252.9 2154.54
   256.3 2155.62   263.3 2159.69   273.7 2164.74   280.3 2169.05   290.7 2173.47
#Mann= 4 ,-1 , 0
       0      .1       0  122.19     .05       0  192.74    .045       0
  216.34      .1       0
Bank Sta=192.74,216.34
XS Rating Curve= 0 ,0
Exp/Cntr=0.3,0.1

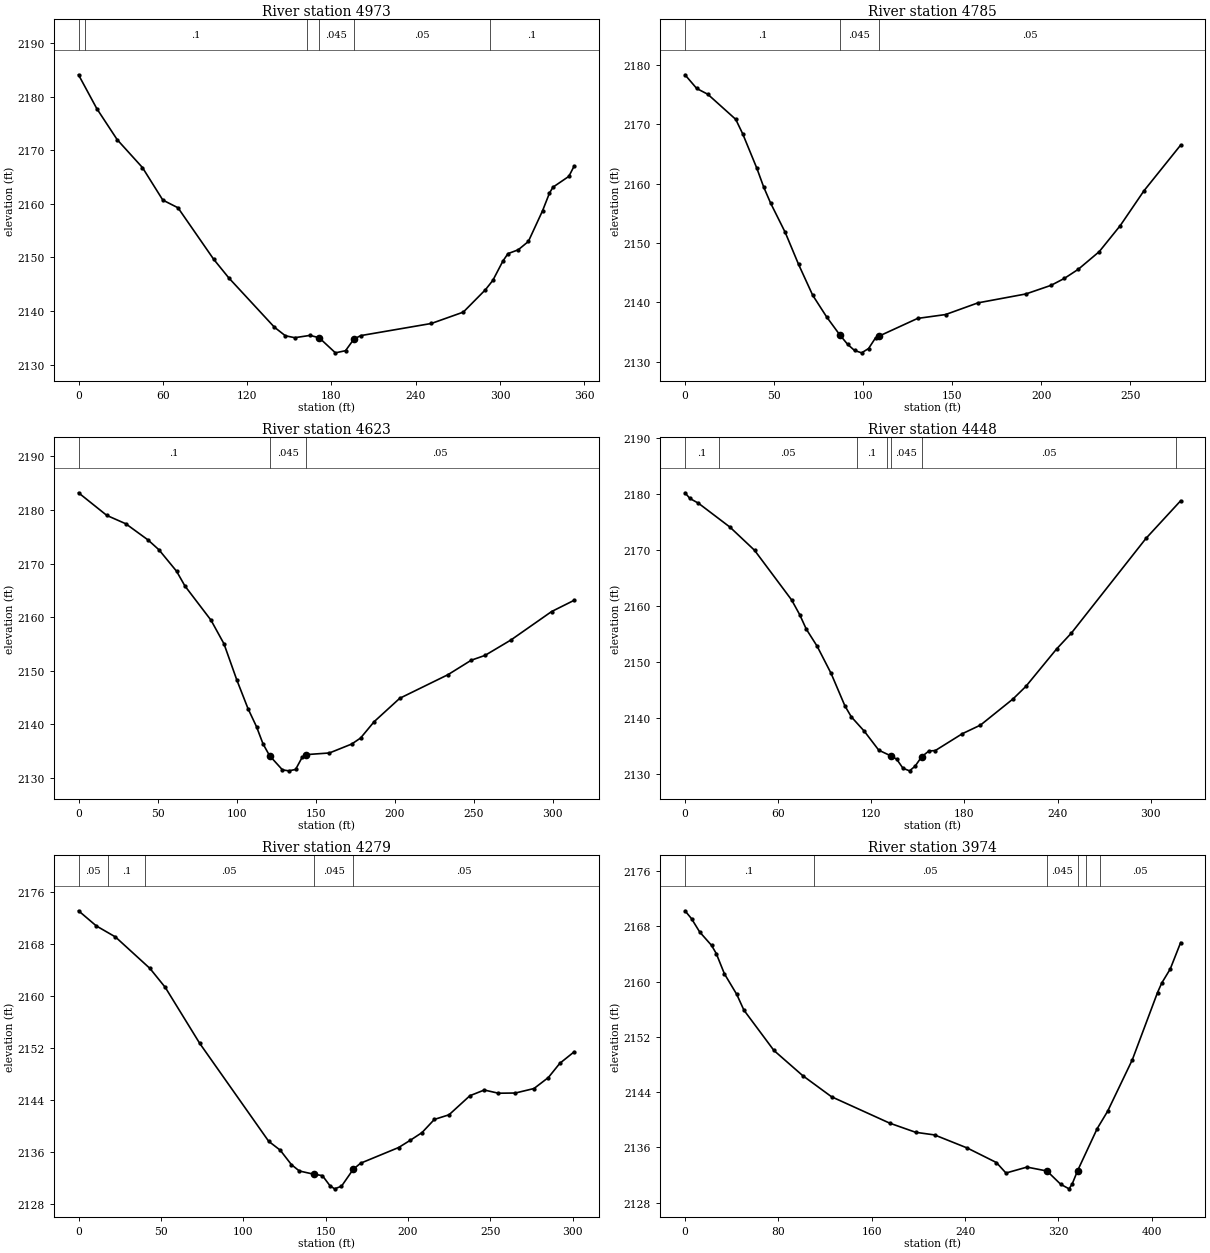
Type RM Length L Ch R = 1 ,4973    ,187.4,188.2,185.2
XS GIS Cut Line= 2
2126985.50556087366223.3266313672126665.19288129366370.895890027
#Sta/Elev= 30
       0 2184.15      13 2177.83    27.5 2172.03    45.5 2166.81      60 2160.73
    70.8 2159.29    96.1  2149.7   106.9  2146.2   139.4 2136.97   147.2 2135.37
   153.9 2135.01   164.7 2135.44  171.222135.008   182.8 2132.18     190 2132.58
  195.932134.737   200.8  2135.4   251.1 2137.67   273.8 2139.79   289.5 2143.96
   294.8 2145.71     302 2149.34   305.6 2150.72   312.9 2151.44   320.1 2152.99
   330.2 2158.73   335.1 2162.02   337.6 2163.14   348.9 2165.16   352.7 2167.09
#Mann= 6 ,-1 , 0
       0      .1       0    4.39      .1       0  162.52     .05       0
  171.22    .045       0  195.93     .05       0  292.47      .1       0
Bank Sta=171.22,195.93
XS Rating Curve= 0 ,0
Exp/Cntr=0.3,0.1

Type RM Length L Ch R = 1 ,4785    ,162.6,162.3,161.2
XS GIS Cut Line= 2
2126876.13045153366083.5696930292126643.49148113366236.347274616
#Sta/Elev= 30
       0 2178.34     6.6 2176.03    12.8 2175.06    28.5 2170.83    32.4  2168.4
    40.3 2162.63    44.2 2159.42    48.1 2156.71    56.3 2151.77    63.8 2146.38
    71.7  2141.2    79.5 2137.56   86.932134.514    91.3 2132.93    95.2 2131.89
    99.2 2131.49   103.1 2132.22     107 2134.02  108.83 2134.29   130.6 2137.29
   146.3 2137.94   164.5 2139.91   191.4 2141.41   205.6 2142.87     213 2144.03
   220.8 2145.56   232.6 2148.54   244.4 2152.93   257.7 2158.79   278.3 2166.49
#Mann= 3 ,-1 , 0
       0      .1       0   86.93    .045       0  108.83     .05       0
Bank Sta=86.93,108.83
XS Rating Curve= 0 ,0
Exp/Cntr=0.3,0.1

Type RM Length L Ch R = 1 ,4623    ,174.4,175.3,174
XS GIS Cut Line= 2
2126807.55414513365926.4515689462126557.55398896 366115.68773903
#Sta/Elev= 30
       0 2183.22    17.9 2178.99    29.9 2177.43      44  2174.4    50.9 2172.56
      62 2168.57    67.3 2165.81    83.8 2159.41      92    2155   100.1 2148.26
   107.2 2142.89   112.6  2139.5   116.7  2136.3  120.852134.094     129 2131.44
     133 2131.26   137.3 2131.52   141.4 2133.76  144.112134.294   158.7  2134.6
   172.8 2136.27   178.4 2137.39     187 2140.45   203.2 2144.82   233.7 2149.23
   248.4 2151.93   257.1 2152.83   273.5 2155.71   299.2 2161.02   313.5 2163.13
#Mann= 3 ,-1 , 0
       0      .1       0  120.85    .045       0  144.11     .05       0
Bank Sta=120.85,144.11
XS Rating Curve= 0 ,0
Exp/Cntr=0.3,0.1

Type RM Length L Ch R = 1 ,4448    ,168.8,168.3,167.9
XS GIS Cut Line= 2
 2126697.3109273365794.5069509452126445.57488221365990.687660947
#Sta/Elev= 30
       0  2180.3     3.2 2179.28     8.7 2178.43      29 2174.16    44.8 2170.03
    68.7 2161.15    73.9 2158.52    78.1 2155.96    85.1  2152.9    94.1 2148.04
     103 2142.24   107.1 2140.29   115.5 2137.71   124.8 2134.33  132.412133.334
   136.3 2132.73   140.4  2131.1   144.6 2130.64   148.2 2131.47  152.432133.157
   157.1 2134.19   161.2 2134.26   178.6 2137.27   190.3 2138.81   211.3 2143.49
   219.5 2145.71   239.3  2152.4   248.9 2155.26   296.9 2172.16   319.2 2178.87
#Mann= 7 ,-1 , 0
       0      .1       0   21.91     .05       0  110.78      .1       0
  129.81     .05       0  132.41    .045       0  152.43     .05       0
  316.47      .1       0
Bank Sta=132.41,152.43
XS Rating Curve= 0 ,0
Exp/Cntr=0.3,0.1

Type RM Length L Ch R = 1 ,4279    ,297.9,304.9,305.9
XS GIS Cut Line= 2
2126589.67203495365656.4862296132126361.37360704365852.666939616
#Sta/Elev= 30
       0 2173.05    10.8 2170.73    22.4 2169.04    43.4  2164.2    52.7 2161.29
    73.6 2152.71   115.5 2137.68   122.5 2136.32   129.3  2134.1   134.1 2133.13
  142.892132.631   148.1 2132.42   152.7 2130.87   155.5 2130.39   159.7 2130.79
  166.86  2133.4   171.3 2134.32   194.4 2136.73   201.6 2137.86   208.6 2139.02
   216.1 2141.04     225 2141.75   237.7 2144.68   246.4 2145.55     255 2145.06
   265.3 2145.09   276.6 2145.78   285.3 2147.46   292.3 2149.65     301 2151.41
#Mann= 5 ,-1 , 0
       0     .05       0   17.77      .1       0   40.33     .05       0
  142.89    .045       0  166.86     .05       0
Bank Sta=142.89,166.86
XS Rating Curve= 0 ,0
Exp/Cntr=0.3,0.1

Type RM Length L Ch R = 1 ,3974    ,261,269.9,278.2
XS GIS Cut Line= 3
2126522.83194554365492.4238937052126313.63059229365575.757060364
2126132.20674255365659.090555117
#Sta/Elev= 30
       0 2170.27     5.6 2169.13    12.6  2167.2    22.8 2165.25    26.8 2164.08
    33.8 2161.14    44.4 2158.15    50.5 2155.88    76.2 2150.04   100.9 2146.39
   125.6 2143.33   175.4 2139.51   197.7 2138.18   213.9  2137.8     242  2135.9
   266.9  2133.8   275.1 2132.28   293.1 2133.14  310.282132.572     322 2130.65
   329.2 2129.99   331.9 2130.71  336.472132.613   353.3 2138.72   362.2 2141.22
   383.4 2148.69     405 2158.43   408.6  2159.8   415.9 2161.84   424.8 2165.66
#Mann= 6 ,-1 , 0
       0      .1       0  110.24     .05       0  310.28    .045       0
  336.47     .05       0  343.73      .1       0  355.52     .05       0
Bank Sta=310.28,336.47
XS Rating Curve= 0 ,0
Exp/Cntr=0.3,0.1

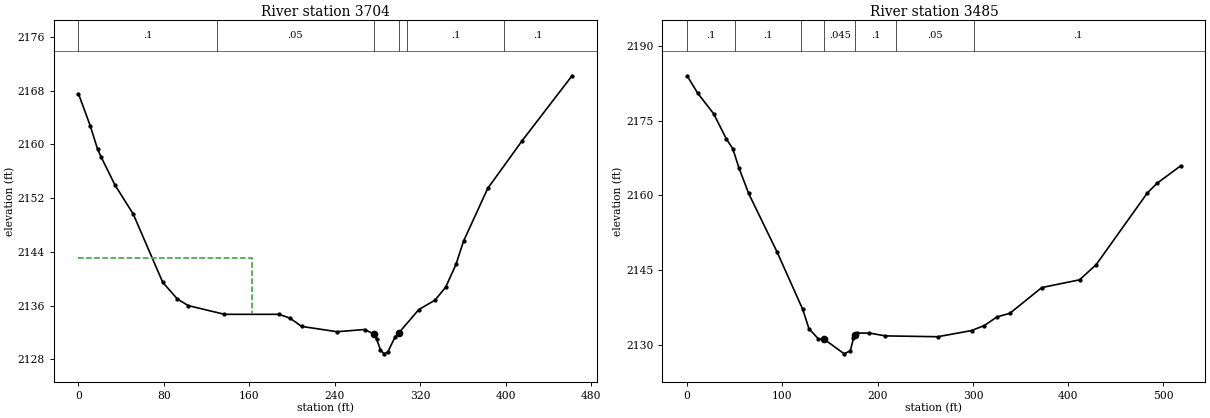
Type RM Length L Ch R = 1 ,3704    ,223.8,219.4,210.1
XS GIS Cut Line= 3
2126488.97768253365438.6044475292126164.32478854 365350.93073836
2126038.45693004365345.722415447
#Sta/Elev= 30
       0 2167.56      11 2162.81    17.9 2159.32    21.3 2158.12    34.3 2153.94
    51.3 2149.65      79 2139.47    92.6 2137.02   102.8 2136.02   136.8 2134.72
   187.8 2134.72     198 2134.16   209.1 2132.92   242.2 2132.13     268 2132.46
  276.372131.821   279.5 2130.98   282.9 2129.39   286.3 2128.84   289.7  2129.1
   296.5 2131.32  300.372132.011   318.8 2135.43   333.9 2136.82   343.9 2138.74
   353.6 2142.14   360.7 2145.61   383.3 2153.44   415.5 2160.53   462.3 2170.21
#Mann= 6 ,-1 , 0
       0      .1       0  129.82     .05       0  276.37    .045       0
  300.37     .05       0  308.12      .1       0  398.35      .1       0
#XS Ineff= 2 , 0
          162.42 2143.07
Permanent Ineff=
       F       F
Bank Sta=276.37,300.37
XS Rating Curve= 0 ,0
Exp/Cntr=0.3,0.1

Type RM Length L Ch R = 1 ,3485    ,292.9,291.7,290.2
XS GIS Cut Line= 3
2126390.88732755365139.9931681162126162.58889961365181.659751445
2125883.07502297365242.423737526
#Sta/Elev= 30
       0 2184.07    11.2 2180.55    27.9 2176.42    41.2 2171.36    47.9 2169.42
    54.6 2165.45    64.6  2160.4    94.6 2148.56   121.3 2137.12   127.9 2133.21
   137.9 2131.15  143.822131.095   164.9 2128.16   171.3 2128.79   174.6 2131.25
   176.52131.861     178 2132.33   191.3 2132.34     208 2131.77     263  2131.6
   298.5 2132.84   311.9 2133.85   325.3 2135.58   338.8 2136.32   372.3 2141.49
   411.9 2143.04   429.4 2146.11   483.1 2160.52   493.2 2162.45   518.1 2165.97
#Mann= 7 ,-1 , 0
       0      .1       0   50.51      .1       0  119.59      .1       0
  143.82    .045       0   176.5      .1       0  218.93     .05       0
   301.5      .1       0
Bank Sta=143.82,176.5
XS Rating Curve= 0 ,0
Exp/Cntr=0.3,0.1