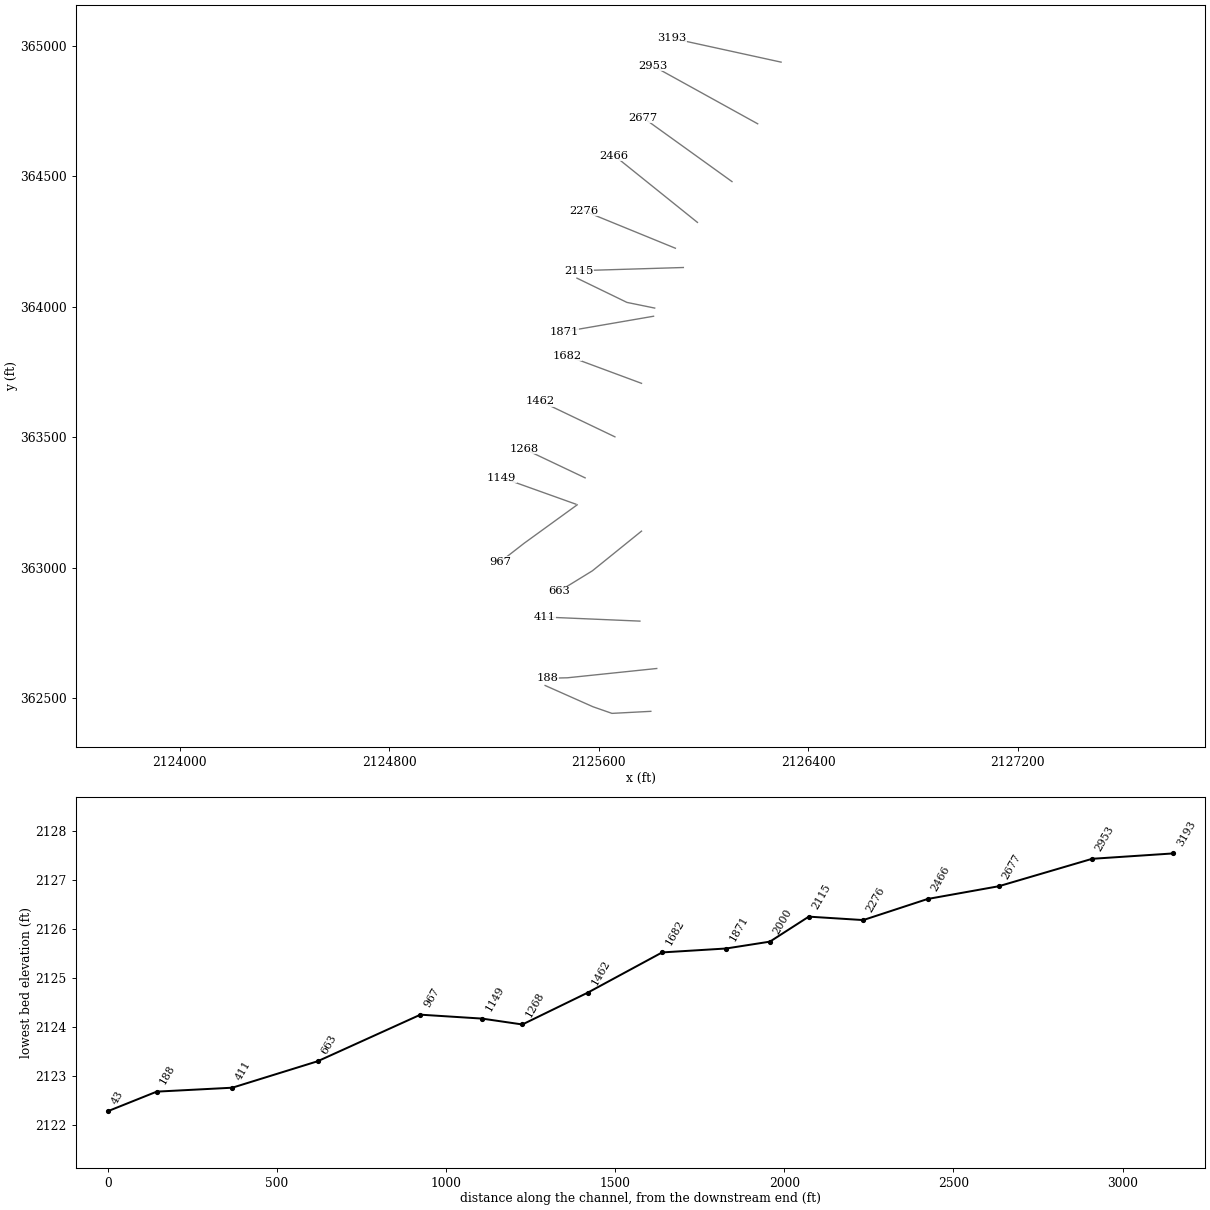
HEC-RAS study INDIANCK.prj: INDIANCK

--- INDIANCK.g01 (geometry) --- (continued)

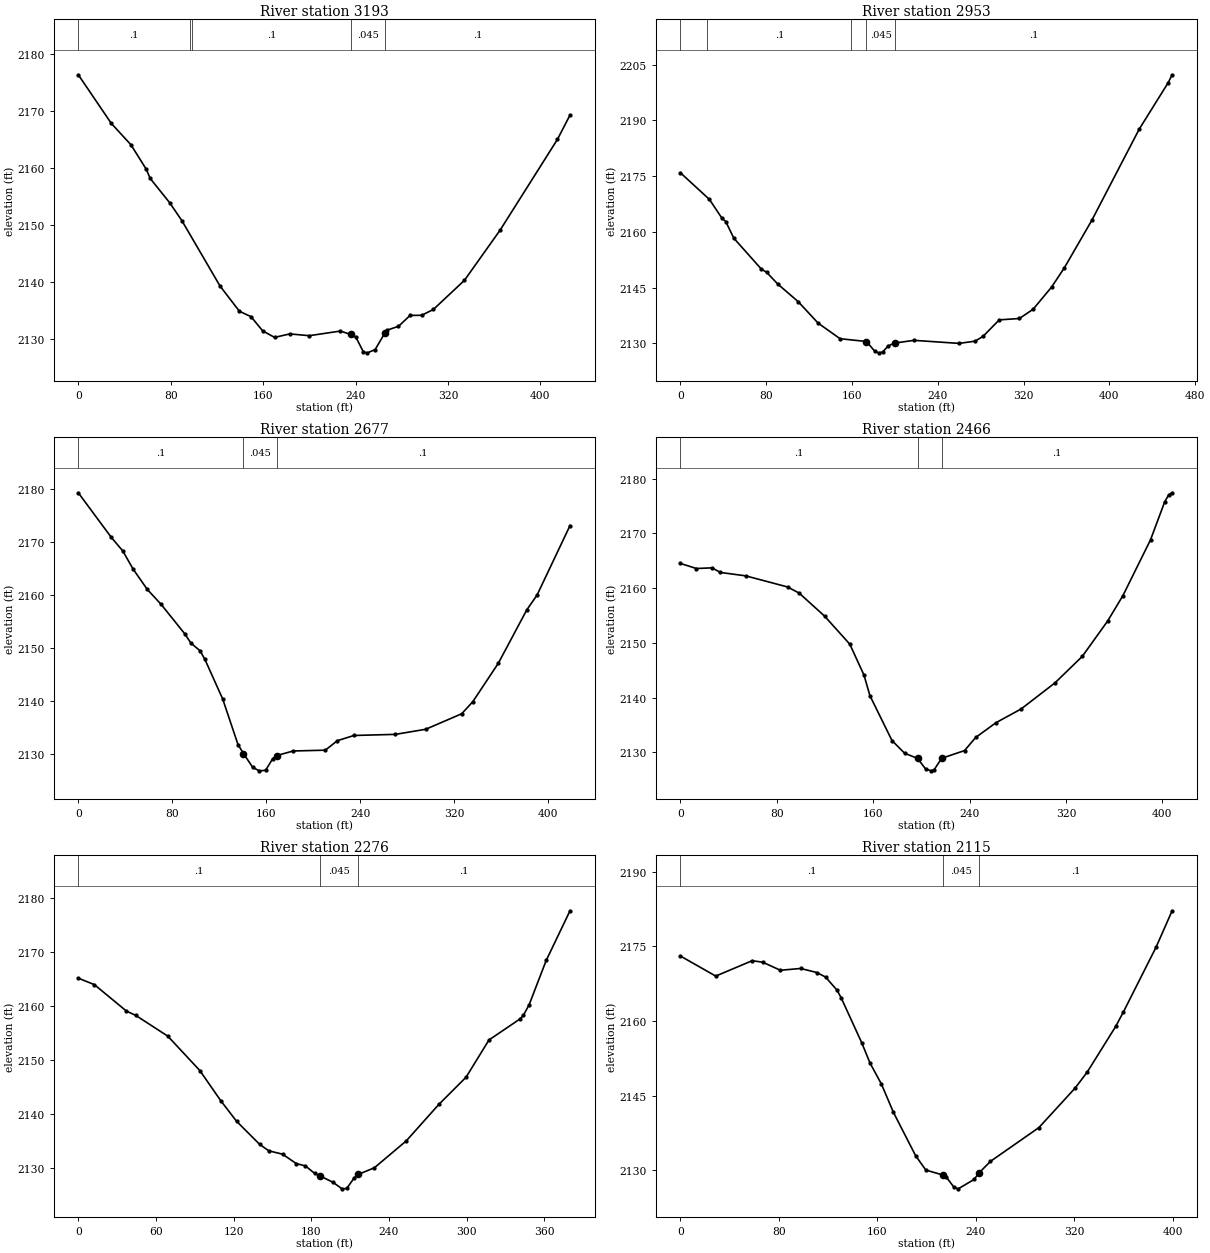
Type RM Length L Ch R = 1 ,3193    ,240,240.3,231.9
XS GIS Cut Line= 2
2126296.26940656364936.8682462872125880.47069746365028.014061362
#Sta/Elev= 30
       0 2176.33    28.6 2167.79    45.6 2164.04    58.9 2159.73    62.2 2158.15
      79 2153.91    89.7 2150.73   122.7 2139.27   139.5 2134.84   149.5  2133.9
   159.6 2131.41   169.9 2130.26   183.1 2130.87     200 2130.56   226.8 2131.37
  235.762130.784   240.2 2130.34   246.9 2127.68   250.3 2127.55     257 2128.12
  265.232130.974   267.1 2131.52   277.2  2132.2   287.2 2134.11   297.3 2134.14
   307.4 2135.16   334.3 2140.27   365.2 2149.08   414.8 2164.99   425.7 2169.26
#Mann= 5 ,-1 , 0
       0      .1       0   96.96      .1       0   98.56      .1       0
  235.76    .045       0  265.23      .1       0
Bank Sta=235.76,265.23
XS Rating Curve= 0 ,0
Exp/Cntr=0.3,0.1

Type RM Length L Ch R = 1 ,2953    ,277.1,276.2,273.2
XS GIS Cut Line= 2
2126206.85948038364700.7571699472125805.81795964364922.979166448
#Sta/Elev= 30
       0 2175.89    27.1  2168.7    38.5 2163.75    42.3 2162.75    49.8 2158.28
    75.5 2149.96    80.3 2149.13      91 2145.89   109.8 2141.22   128.5 2135.41
   148.9 2131.24   173.5 2130.49   181.1 2127.92   184.8 2127.44   188.6 2127.65
   193.7 2129.31  199.772130.077   217.9  2130.8   259.8 2129.98   274.8 2130.58
   282.3  2131.9   297.3 2136.31   316.1 2136.68   328.9 2139.17   346.1 2145.13
   357.9 2150.26   383.6 2163.08   427.8 2187.61   454.9 2200.15   458.5 2202.25
#Mann= 5 ,-1 , 0
       0      .1       0   25.02      .1       0   159.5      .1       0
   173.5    .045       0  199.77      .1       0
Bank Sta=173.5,199.77
XS Rating Curve= 0 ,0
Exp/Cntr=0.3,0.1

Type RM Length L Ch R = 1 ,2677    ,212.5,210.4,208.9
XS GIS Cut Line= 2
2126108.76945347364479.4029538632125769.35969922364724.194459036
#Sta/Elev= 30
       0 2179.25    27.8 2170.93    37.9 2168.28    46.6 2164.89    58.7 2161.05
    70.3 2158.28    90.5 2152.72      96  2150.9   103.6  2149.5   107.7 2147.89
   122.9 2140.41   135.9 2131.84  140.582130.136   148.5 2127.52   154.1 2126.88
   159.4 2126.98   165.3 2129.11  168.74 2129.75   182.9 2130.62   210.2 2130.77
   220.5 2132.56   234.6 2133.54   269.9 2133.75   295.7 2134.71   326.3 2137.63
   335.7 2139.88   357.5 2147.15   381.7 2157.19   390.4 2159.96   418.5 2173.07
#Mann= 3 ,-1 , 0
       0      .1       0  140.58    .045       0  168.74      .1       0
Bank Sta=140.58,168.74
XS Rating Curve= 0 ,0
Exp/Cntr=0.3,0.1

Type RM Length L Ch R = 1 ,2466    ,185.4,190.1,193.6
XS GIS Cut Line= 2
2125976.82483545364323.1529382772125659.11648136364579.229197785
#Sta/Elev= 30
       0 2164.49    13.3 2163.57    26.2 2163.69    33.2 2162.85    54.2 2162.23
    89.1 2160.19    98.6 2159.07   119.6 2154.89   140.6 2149.75   152.4 2144.08
   157.3 2140.34   175.6 2132.15   186.1 2129.83  196.832128.893   203.6 2126.93
   208.2 2126.62   210.6 2126.83  216.852128.915   235.8 2130.32   245.1 2132.72
   261.9 2135.41   282.8 2137.92   310.9 2142.69   333.5 2147.51   354.6 2153.98
   367.3 2158.63   390.2 2168.82   401.9 2175.72   405.2    2177   408.1  2177.4
#Mann= 3 ,-1 , 0
       0      .1       0  196.83    .045       0  216.85      .1       0
Bank Sta=196.83,216.85
XS Rating Curve= 0 ,0
Exp/Cntr=0.3,0.1

Type RM Length L Ch R = 1 ,2276    ,153.9,161,166.2
XS GIS Cut Line= 2
2125892.62356028364224.1944747872125541.06094322364368.291627526
#Sta/Elev= 30
       0  2165.1    12.4 2163.91    37.2 2159.02    44.3 2158.24    69.1  2154.4
    93.9 2148.04     110 2142.49   122.3 2138.66     140 2134.43   147.1 2133.22
   157.8 2132.59   168.4 2130.86   175.5 2130.42   182.6 2129.04   186.72128.593
   196.8 2127.39   203.8 2126.19   207.4 2126.26   213.1  2128.2  216.182128.848
   228.7 2130.07   253.4 2135.05   278.5 2141.77   299.6 2146.81   317.3 2153.69
   341.4 2157.59   343.9 2158.25   348.3 2160.18   361.5 2168.37   379.9 2177.55
#Mann= 3 ,-1 , 0
       0      .1       0   186.7    .045       0  216.18      .1       0
Bank Sta=186.7,216.18
XS Rating Curve= 0 ,0
Exp/Cntr=0.3,0.1

Type RM Length L Ch R = 1 ,2115    ,119.3,114.9,104.3
XS GIS Cut Line= 2
 2125923.0053893364150.4098454422125523.69975746 364138.25698261
#Sta/Elev= 30
       0 2173.03    28.7    2169    58.3 2172.09    66.9 2171.79    81.2 2170.17
    97.7 2170.53   110.8 2169.72   117.9 2168.81   127.2 2166.19   130.5 2164.69
   147.3 2155.62     154 2151.56   163.3 2147.31   173.1 2141.61   191.1 2132.92
   199.4 2130.03  213.072129.054   215.8 2128.69   222.4 2126.54   225.7 2126.26
   238.7 2128.16  242.312129.379   251.9 2131.78   291.3 2138.57   320.9 2146.56
   330.7 2149.78   353.7  2158.9     360 2161.83   386.5 2174.82   399.5 2182.12
#Mann= 3 ,-1 , 0
       0      .1       0  213.07    .045       0  242.31      .1       0
Bank Sta=213.07,242.31
XS Rating Curve= 0 ,0
Exp/Cntr=0.3,0.1

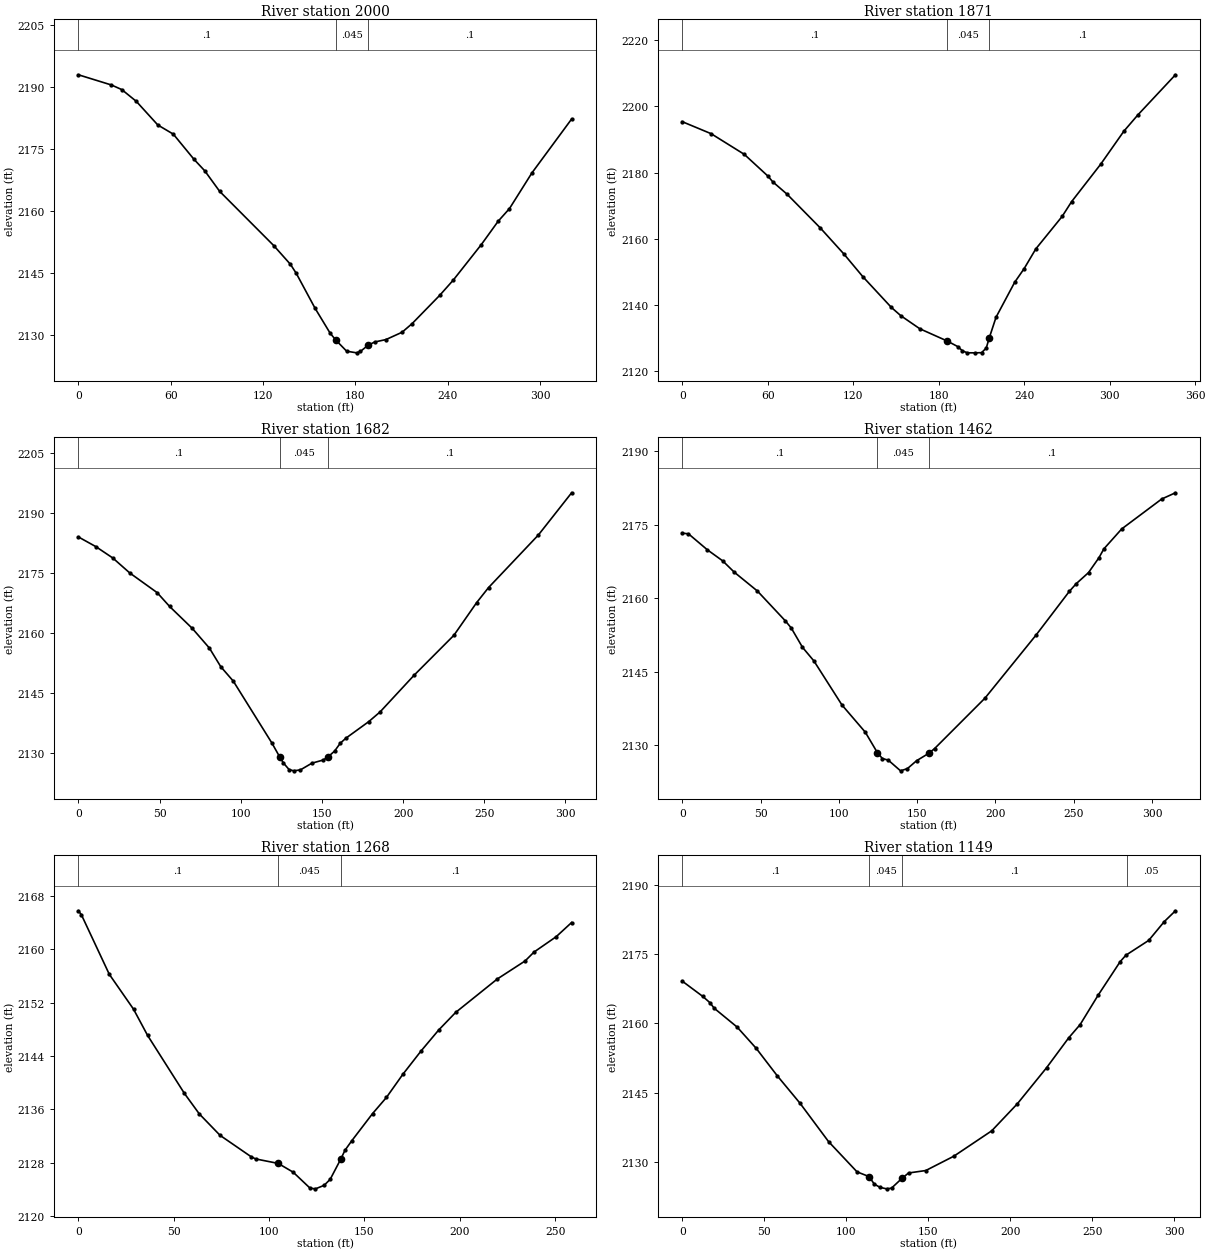
Type RM Length L Ch R = 1 ,2000    ,119.7,129.6,136.4
XS GIS Cut Line= 3
2125813.63060805363995.0279383662125707.72760463364016.729338527
2125516.75554562364109.611370608
#Sta/Elev= 30
       0 2192.94    21.5 2190.47    28.2 2189.36    37.6 2186.53    51.6 2180.81
    61.7 2178.59    75.1 2172.52    82.1 2169.74    91.8 2164.77   126.9 2151.68
   137.8 2147.13   141.6 2144.94   153.8 2136.51   163.6 2130.49  167.482128.754
   174.3 2126.15   180.8 2125.75   183.3  2126.1  188.122127.555   192.5 2128.37
   199.8 2128.95   210.3 2130.72   216.8 2132.79   234.8 2139.65   243.6 2143.33
   261.8  2151.9   272.8 2157.57   280.1  2160.6   294.7 2169.23   320.5 2182.25
#Mann= 3 ,-1 , 0
       0      .1       0  167.48    .045       0  188.12      .1       0
Bank Sta=167.48,188.12
XS Rating Curve= 0 ,0
Exp/Cntr=0.3,0.1

Type RM Length L Ch R = 1 ,1871    ,192.4,189,176.6
XS GIS Cut Line= 2
2125809.29006556363963.7780008612125468.14442238363904.750231788
#Sta/Elev= 30
       0 2195.38    20.3 2191.75    43.6 2185.51    60.2 2178.94    63.6 2177.21
    73.6 2173.49    96.9 2163.32   113.5 2155.44   126.8 2148.59   146.8 2139.32
   153.5  2136.8   166.8 2132.87  186.172129.146   193.4  2127.5   196.7 2126.22
   200.1 2125.62   205.7 2125.61   210.1 2125.66   213.4 2127.04  215.572130.184
   220.3 2136.37   233.4 2146.93     240 2151.02   248.2 2156.98   266.7 2166.79
   273.3 2171.23   293.7 2182.52     310  2192.5   319.9 2197.45   346.2 2209.53
#Mann= 3 ,-1 , 0
       0      .1       0  186.17    .045       0  215.57      .1       0
Bank Sta=186.17,215.57
XS Rating Curve= 0 ,0
Exp/Cntr=0.3,0.1

Type RM Length L Ch R = 1 ,1682    ,219.4,219.7,216.7
XS GIS Cut Line= 2
 2125763.2832678363706.8333047782125478.56106821363812.736308202
#Sta/Elev= 30
       0 2184.05    10.7 2181.64    21.2 2178.78    31.7 2175.02    48.5 2170.12
    56.2 2166.65    70.2 2161.15    80.7 2156.24    87.7 2151.58    95.4 2147.98
   119.2 2132.48  124.12 2128.92   126.3 2127.48   129.8 2125.84   132.7 2125.53
   136.8 2125.78   143.8 2127.44   150.8 2128.24  153.522128.938   157.8 2130.47
   161.3 2132.44   164.8 2133.71   178.8 2137.83   185.8 2140.26   206.7 2149.42
   231.3 2159.45   245.3 2167.62   252.6 2171.37   283.3 2184.53   303.8  2195.1
#Mann= 3 ,-1 , 0
       0      .1       0  124.12    .045       0  153.52      .1       0
Bank Sta=124.12,153.52
XS Rating Curve= 0 ,0
Exp/Cntr=0.3,0.1

Type RM Length L Ch R = 1 ,1462    ,192.9,193.5,193.1
XS GIS Cut Line= 2
2125661.72080687363501.9724940362125377.86671579 363638.25699836
#Sta/Elev= 30
       0  2173.3       4 2173.16      16 2169.91    25.9 2167.62    33.2 2165.33
      48 2161.47    65.9 2155.35    69.6 2153.92    76.8 2149.96    84.1 2147.17
     102 2138.17   116.9 2132.61  124.642128.414   127.8 2127.23   131.6 2126.89
   139.4 2124.71   143.8 2125.17   149.6 2126.77  157.442128.297   161.1 2129.25
   193.3 2139.57     226  2152.5   247.1 2161.37   251.5 2162.95   259.4 2165.23
   266.1 2168.29   269.2 2170.08   280.6 2174.16   306.1 2180.27   314.9 2181.55
#Mann= 3 ,-1 , 0
       0      .1       0  124.64    .045       0  157.44      .1       0
Bank Sta=124.64,157.44
XS Rating Curve= 0 ,0
Exp/Cntr=0.3,0.1

Type RM Length L Ch R = 1 ,1268    ,117.6,119.2,120.7
XS GIS Cut Line= 2
2125548.00548312363344.854369953 2125314.4984042363455.965368196
#Sta/Elev= 30
       0 2165.78     1.6 2165.17    16.2 2156.25    28.9 2151.02    36.3 2147.07
    55.6 2138.37    63.4  2135.3    74.3 2132.08    90.4 2128.91    92.9 2128.55
  104.752127.875   112.6 2126.56   121.5 2124.15   124.3 2124.06   128.8 2124.58
     132 2125.48  137.482128.477   139.8 2129.86   143.3 2131.26   154.2 2135.34
   161.5 2137.77   170.1 2141.24   179.7 2144.76   188.9 2147.89   197.8 2150.53
   219.6 2155.54   234.2 2158.25   238.9 2159.59   250.5 2161.89   258.6 2164.02
#Mann= 3 ,-1 , 0
       0      .1       0  104.75    .045       0  137.48      .1       0
Bank Sta=104.75,137.48
XS Rating Curve= 0 ,0
Exp/Cntr=0.3,0.1

Type RM Length L Ch R = 1 ,1149    ,171.4,182.1,203.6
XS GIS Cut Line= 2
2125512.41533121363244.1596894412125229.42902055363345.722478449
#Sta/Elev= 30
       0 2169.12    12.6 2165.79    16.9 2164.45    19.5 2163.25    33.5 2159.17
    45.1 2154.58    57.9 2148.66    71.8 2142.71    89.2 2134.41   106.6 2127.85
  113.912126.833   117.1 2125.21   120.6  2124.5   124.6 2124.18   127.6 2124.33
     1342126.453     138 2127.61   148.5 2128.14   165.6 2131.24   188.7 2136.73
   204.3 2142.57   222.1 2150.36   235.6 2156.83   242.6 2159.71   253.5 2166.03
     267 2173.32   270.5 2174.72   284.4 2177.92   293.9 2181.99   300.7 2184.33
#Mann= 4 ,-1 , 0
       0      .1       0  113.91    .045       0     134      .1       0
  271.07     .05       0
Bank Sta=113.91,134
XS Rating Curve= 0 ,0
Exp/Cntr=0.3,0.1

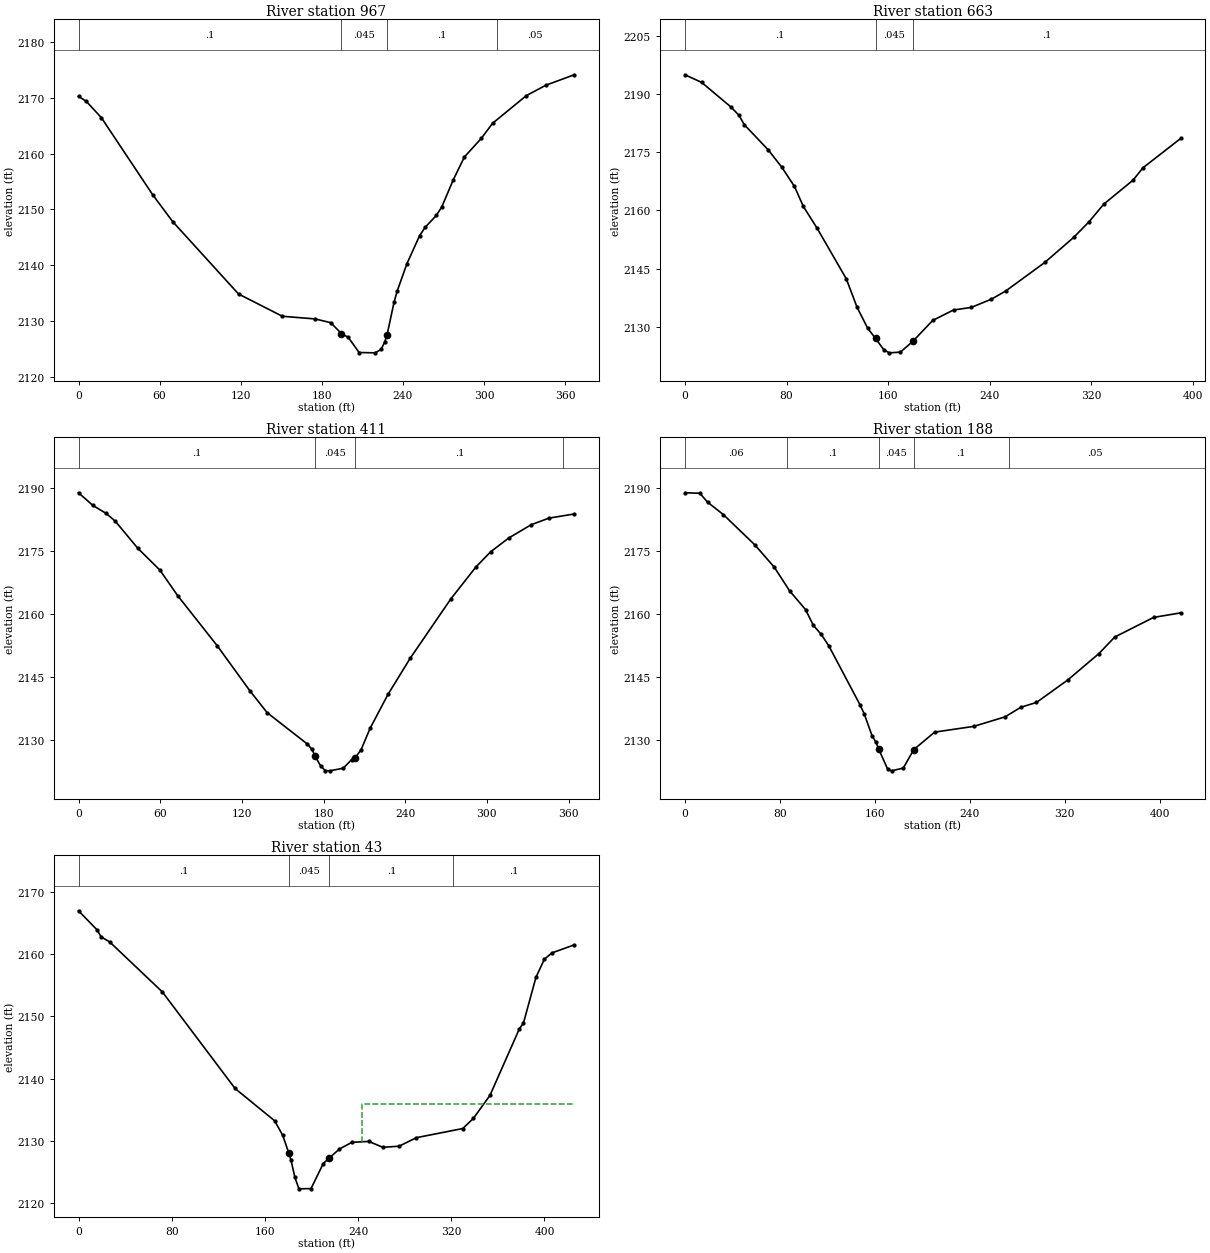
Type RM Length L Ch R = 1 ,967     ,304.8,303.8,308.9
XS GIS Cut Line= 3
2125517.62365413363241.555692032 2125314.4984042363093.986105278
2125223.35258913363022.805801451
#Sta/Elev= 30
       0 2170.26     5.7 2169.38      17 2166.41      55 2152.57    69.7 2147.79
   118.4 2134.81   150.8 2130.82   175.1 2130.34   186.6 2129.67  194.512127.713
   199.5 2127.06   207.6 2124.32   219.4 2124.26   223.8 2124.86   226.5 2126.17
  228.252127.461   233.5 2133.39   235.7 2135.29   242.9 2140.21   252.4  2145.3
   256.4 2146.75   264.7  2148.9   268.7  2150.4   277.2 2155.26   285.5 2159.39
     298 2162.73   306.3 2165.42   331.3 2170.39   345.8 2172.26   366.7 2174.13
#Mann= 4 ,-1 , 0
       0      .1       0  194.51    .045       0  228.25      .1       0
  309.28     .05       0
Bank Sta=194.51,228.25
XS Rating Curve= 0 ,0
Exp/Cntr=0.3,0.1

Type RM Length L Ch R = 1 ,663     ,262.3,252.4,240.6
XS GIS Cut Line= 3
 2125763.2832678363140.861339614 2125575.7833147362988.951538444
2125449.04701963362910.826366618
#Sta/Elev= 30
       0 2194.94    13.1 2192.98    36.4 2186.58    42.5  2184.5    46.7 2182.08
    65.4 2175.64    76.1 2171.19    86.2 2166.17    93.2 2161.02   104.1 2155.36
     127 2142.38   135.4  2135.1   143.8 2129.66  150.012127.012   156.5 2124.13
   160.7 2123.31   169.6 2123.49  179.362126.263     195 2131.65   211.4 2134.35
   225.4 2135.01   241.3 2137.14   252.6 2139.26   283.4 2146.63   306.1 2153.08
   318.1 2157.07   329.6 2161.59   352.8 2167.81   360.5 2170.96   390.2 2178.53
#Mann= 3 ,-1 , 0
       0      .1       0  150.01    .045       0  179.36      .1       0
Bank Sta=150.01,179.36
XS Rating Curve= 0 ,0
Exp/Cntr=0.3,0.1

Type RM Length L Ch R = 1 ,411     ,222.6,223.3,226.8
XS GIS Cut Line= 2
2125757.20683637362796.2432624552125393.49168456362811.868231192
#Sta/Elev= 30
       0 2188.98    10.6 2185.96    20.4 2184.05      27 2182.22    43.4 2175.82
    59.8 2170.56      73 2164.42     102 2152.51     126 2141.78   138.6 2136.61
   168.2 2129.13   171.5 2127.89  173.832126.245     178 2123.86   181.3 2122.84
   184.6 2122.77   194.5  2123.4   200.6 2125.44  203.34 2125.91   207.6 2127.82
   214.2  2132.9   227.3 2140.95   243.7  2149.6   273.5 2163.71   291.9  2171.3
   302.8 2174.94     316  2178.2   332.4 2181.35   345.5 2182.94   364.1 2183.93
#Mann= 4 ,-1 , 0
       0      .1       0  173.83    .045       0  203.34      .1       0
  356.15     .05       0
Bank Sta=173.83,203.34
XS Rating Curve= 0 ,0
Exp/Cntr=0.3,0.1

Type RM Length L Ch R = 1 ,188     ,151.3,144.8,138.3
XS GIS Cut Line= 3
2125821.44292837362614.819412693 2125480.2972852362579.229260787
2125405.64421928 362577.49304378
#Sta/Elev= 30
       0 2188.84    12.5 2188.73    19.1 2186.59    32.3 2183.66    58.7  2176.5
    75.2 2171.16    88.4 2165.42   101.6 2161.06   108.2 2157.29   114.8 2155.17
   121.4 2152.32   147.8 2138.24   151.1 2136.21   157.7 2130.99     161 2129.48
  163.332127.798   170.9 2123.04   174.1 2122.69     184 2123.35  192.732127.717
   210.4  2131.9   243.4 2133.27   269.8 2135.54     283 2137.81   296.2 2138.96
   322.6 2144.31   348.9  2150.6   362.1 2154.51   394.9 2159.19   417.7 2160.27
#Mann= 5 ,-1 , 0
       0     .06       0    85.8      .1       0  163.33    .045       0
  192.73      .1       0  272.83     .05       0
Bank Sta=163.33,192.73
XS Rating Curve= 0 ,0
Exp/Cntr=0.3,0.1

Type RM Length L Ch R = 1 ,43      ,43.69,42.88,42.08
XS GIS Cut Line= 4
 2125798.8734197362450.7570767852125650.43605253362442.944428369
2125578.38731211362468.1182625292125395.22757345362549.715540275
#Sta/Elev= 30
       0 2166.96    16.1 2163.86    19.4 2162.77    26.8 2161.95      72 2153.92
   134.4 2138.41   168.4 2133.22   175.3 2130.89  180.442128.083   182.3    2127
   185.7 2124.17   189.2 2122.29   199.6 2122.33   210.1 2126.35  215.422127.273
     224 2128.69   234.7 2129.76   249.1 2129.91   261.3 2128.96   275.2 2129.14
   290.1 2130.51   329.9 2131.98   338.9 2133.59   353.2  2137.3   378.4 2147.97
     382 2148.94   392.7 2156.27   399.9 2159.17   406.4 2160.19   425.5 2161.48
#Mann= 4 ,-1 , 0
       0      .1       0  180.44    .045       0  215.42      .1       0
  321.81      .1       0
#XS Ineff= 1 ,-1
  243.63  425.48 2135.95
Permanent Ineff=
       F
Bank Sta=180.44,215.42
XS Rating Curve= 0 ,0
Exp/Cntr=0.3,0.1
LCMann Table=0

Chan Stop Cuts=-1
Use User Specified Reach Order=0
Composite Channel Slope=5